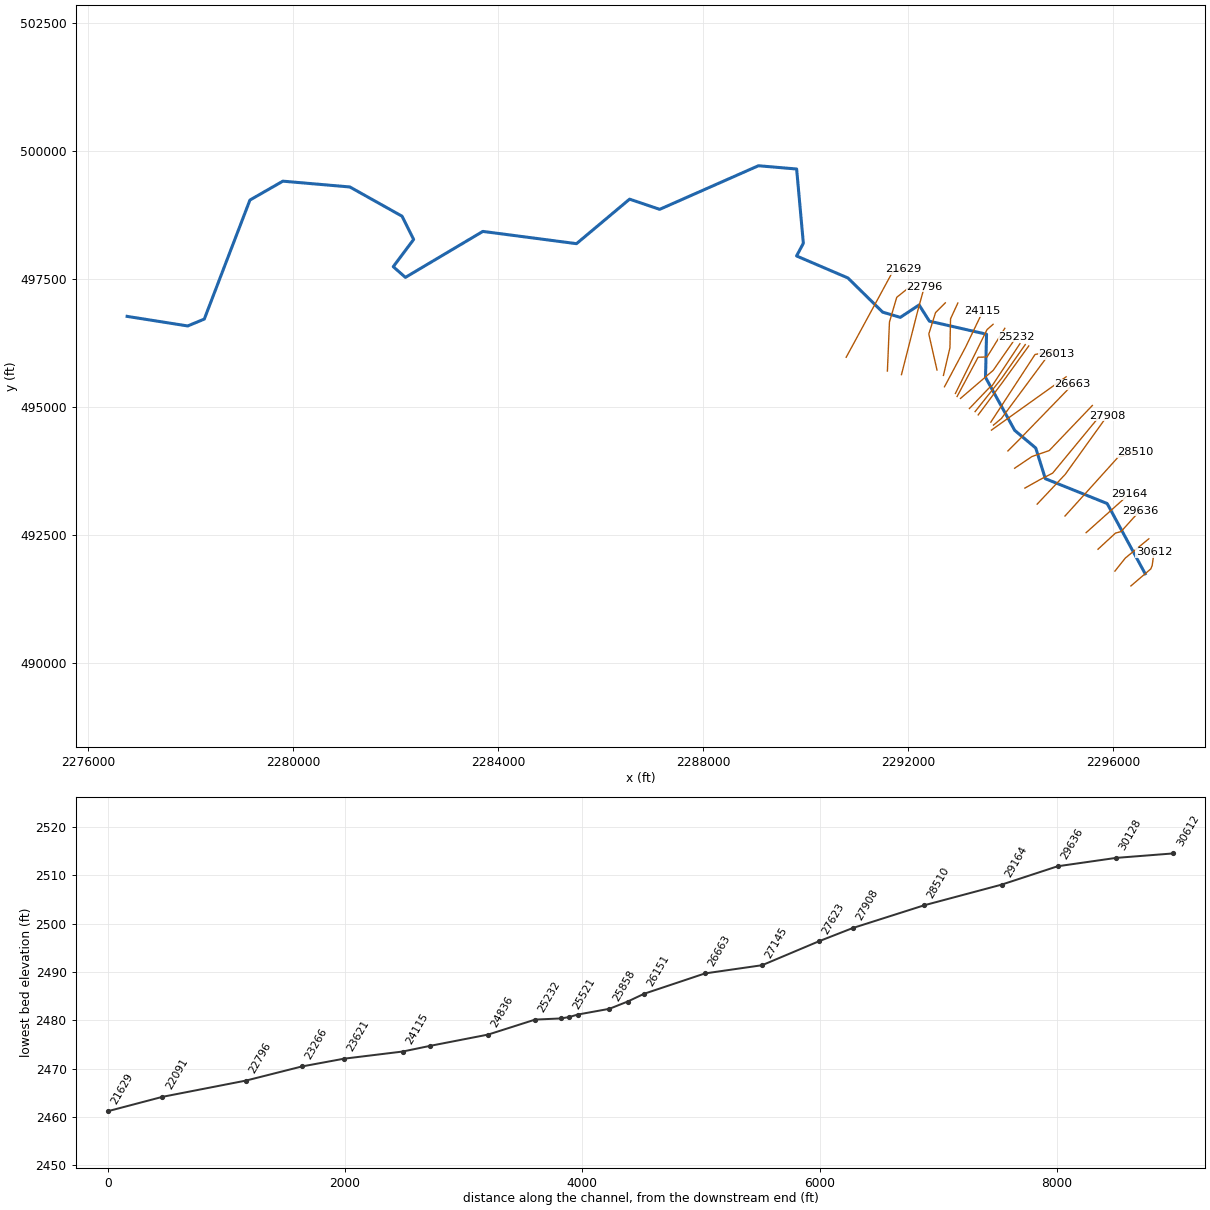
--- SITLNGTNCK.prj (project) ---

Proj Title=SITLNGTNCK
Current Plan=p01
Default Exp/Contr=0,0
English Units
Geom File=g01
Flow File=f01
Plan File=p01
Background Map Layer=Inundation Boundary (01pct Value_0)
BEGIN DESCRIPTION:
----------MODEL BY WOOD PLC 2021----------
Stream Name: Sitlington Creek
Flood Zone: Enhanced Approximate
Pocahontas County, WV
HEC-RAS Version: RAS 6.1
Vertical Datum: NAVD88
Projection: NAD 1983 StatePlane West Virginia S FIPS 4702 (US Feet)
Terrain: 1-meter LIDAR (FEMA Region III 3DEP collected 2016-2018)
Land Use: 2019 NLCD
Hydrologic Method:
WV SIR2010-5033 regression equations
Model Notes:
normal depth tie in to Greenbrier River
END DESCRIPTION:
DSS Export Rating Curves= 0
DSS Export Rating Curve Sorted= 0
DSS Export Volume Flow Curves= 0
DXF OffsetX= 0
DXF OffsetY= 0
DXF ScaleX= 0
DXF ScaleY= 0

--- SITLNGTNCK.p01 (plan) ---

Plan Title=Floodplain
Program Version=6.00
Short Identifier=Floodplain
Geom File=g01
Flow File=f01
Subcritical Flow
K Sum by GR= 0
Std Step Tol= 0.01
Critical Tol= 0.01
Num of Std Step Trials= 20
Max Error Tol= 0.3
Flow Tol Ratio= 0.001
Split Flow NTrial= 30
Split Flow Tol= 0.02
Split Flow Ratio= 0.02
Log Output Level= 0
Friction Slope Method= 1
Unsteady Friction Slope Method= 2
Unsteady Bridges Friction Slope Method= 1
Parabolic Critical Depth
Global Vel Dist= 0 , 0 , 0
Global Log Level= 0
CheckData=True
Encroach Param=-1 ,0,0, 0
Mapping Interval=1HOUR
Computation Time Step Use Courant=        0
Computation Time Step Use Time Series=    0
Computation Time Step Count To Double=0
Computation Time Step Max Doubling=0
Computation Time Step Max Halving=0
Computation Time Step Residence Courant=0
Run HTab= 0
Run UNet= 0
Run Sediment= 0
Run PostProcess= 0
Run WQNet= 0
Run RASMapper=-1
UNET Theta= 0
UNET Theta Warmup= 0
UNET ZTol= 0
UNET ZSATol= 0
UNET MxIter= 0
UNET Max Iter WO Improvement= 0
UNET MaxInSteps= 0
UNET DtIC= 0
UNET DtMin= 0
UNET MaxCRTS= 0
UNET WFStab= 0
UNET SFStab= 0
UNET WFX= 1
UNET SFX= 1
UNET Gravity=32.174
UNET 1D Methodology=Finite Difference
UNET DSS MLevel= 1
UNET Pardiso=0
UNET DZMax Abort= 0
UNET Use Existing IB Tables= 0
UNET Froude Reduction=False
UNET Froude Limit= 0
UNET Froude Power= 0
UNET D1 Cores= 0
UNET WindReference=Eulerian
UNET WindDragFormulation=Hsu (1988)
UNET D2 Coriolis=0
UNET D2 Cores= 0
UNET D2 Theta= 1
UNET D2 Theta Warmup= 1
UNET D2 Z Tol= 0.01
UNET D2 Volume Tol= 0.01
UNET D2 Max Iterations= 20
UNET D2 Equation= 0
UNET D2 RampUpFraction=0.1
UNET D2 TimeSlices= 1
UNET D2 Turbulence Formulation=Non-Conservative (original)
UNET D2 Eddy Viscosity=0.3
UNET D2 Transverse Eddy Viscosity=0.1
UNET D2 Smagorinsky Mixing=0
UNET D2 BCVolumeCheck=0
UNET D2 Cores=0
UNET D2 SolverType=PARDISO (Direct)
UNET D2 Minimum Iterations= 2147483647
UNET D2 Maximum Iterations= 2147483647
UNET D2 Restart Number= 10
UNET D2 Relaxation Coeff=1.3
UNET D2 SOR Precondition Iterations= 10
UNET D2 ILUT Maximum Fill= 8
UNET D2 ILUT Tolerance=1E-08
UNET D1D2 MaxIter= 0
UNET D1D2 ZTol=0.01
UNET D1D2 QTol=0.1
UNET D1D2 MinQTol=1
Write IC File= 0
Write IC File at Fixed DateTime=0
Write IC File at Sim End=0
Echo Input=False
Echo Parameters=False
Echo Output=False
Write Detailed= 0
HDF Write Warmup=0
HDF Write Time Slices=0
HDF Flush=0
HDF Compression= 1
HDF Chunk Size= 1
HDF Spatial Parts= 1
HDF Use Max Rows=0
HDF Fixed Rows= 1
Calibration Method= 0
Calibration Iterations= 20
Calibration Max Change=0.05
Calibration Tolerance=0.2
Calibration Maximum=1.5
Calibration Minimum=0.5
Calibration Optimization Method= 1
WQ AD Non Conservative
WQ ULTIMATE=-1
WQ Max Comp Step=1HOUR
WQ Output Interval=15MIN
WQ Output Selected Increments= 0
WQ Output face flow=0
WQ Output face velocity=0
WQ Output face area=0
WQ Output face dispersion=0
WQ Output cell volume=0
WQ Output cell surface area=0
WQ Output cell continuity=0
WQ Output cumulative cell continuity=0
WQ Output face conc=0
WQ Output face dconc_dx=0
WQ Output face courant=0
WQ Output face peclet=0
WQ Output face adv mass=0
WQ Output face disp mass=0
WQ Output cell mass=0
WQ Output cell source sink temp=0
WQ Output nsm pathways=0
WQ Output nsm derived pathways=0
WQ Create Restart=0
WQ Fixed Restart=0
WQ System Summary=0
WQ Write To DSS=0
Sorting and Armoring Iterations= 10
XS Update Threshold= 0.02
Bed Roughness Predictor= 0
Hydraulics Update Threshold= 0.02
Energy Slope Method= 1
Volume Change Method= 1
Sediment Retention Method= 0
Sediment TS Multiplier= 1
Warm Up Method= 0
XS Weighting Method= 0
Number of US Weighted Cross Sections= 1
Number of DS Weighted Cross Sections= 1
Upstream XS Weight=0
Main XS Weight=1
Downstream XS Weight=0
Number of DS XS's Weighted with US Boundary= 1
Upstream Boundary Weight= 1
Weight of XSs Associated with US Boundary= 0
Number of US XS's Weighted with DS Boundary= 1
Downstream Boundary Weight= 0.5
Weight of XSs Associated with DS Boundary= 0.5
Percentile Method= 0
Sediment Output Level= 3
Mass or Volume Output= 0
Output Increment Type= 1
Profile and TS Output Increment= 1
Transport Output Increment 1
XS Output Flag= 0
XS Output Increment= 10
Read HDF5 Sediment Hotstart= 0
Sediment Hotstart Type= 0
Write Gradation File= 0
Read Gradation Hotstart= 0
Write HDF5 File= 1
Write Binary Output= 1
Write DSS Sediment File= 0
DSS Sediment Output Type= 1
SV Curve= 0
Specific Gage Flag= 0
Subcell Erosion Methods= 0
Subcell Deposition Methods= 0
Advection Scheme= 1
Matrix Solver= 0
Implicit Weighting Factor= 1
Maximum Outer Loop Convergence Iterations= 5
Convergence Maximum Absolute= 0.001
Convergence RMSE= 0.0001
Grain Fractions Max Abs Error= 0.001
Max Subgrid Regions= 1
Max Subgrid Length Scale= 3.402823E+38
Initial Layer Thickness= 3.402823E+38
Min Layer Thickness= 3.402823E+38
Max Layer Thickness= 3.402823E+38
Number of Layers= 5

--- SITLNGTNCK.f01 (steady flow) ---

Flow Title=Flow
Program Version=6.10
Number of Profiles= 6
Profile Names=01pct,10pct,04pct,02pct,0_2pct,01plus
River Rch & RM=GALFRDSITLNGTN,Main            ,30612
    4900    2810    3590    4220    6570    7240
River Rch & RM=GALFRDSITLNGTN,Main            ,17634
    5640    3260    4150    4870    7550    8340
River Rch & RM=GALFRDSITLNGTN,Main            ,9041
    6790    3950    5010    5870    9050   10000
Boundary for River Rch & Prof#=GALFRDSITLNGTN,Main            , 1
Up Type= 0
Dn Type= 3
Dn Slope=0.01322
Boundary for River Rch & Prof#=GALFRDSITLNGTN,Main            , 2
Up Type= 0
Dn Type= 3
Dn Slope=0.01322
Boundary for River Rch & Prof#=GALFRDSITLNGTN,Main            , 3
Up Type= 0
Dn Type= 3
Dn Slope=0.01322
Boundary for River Rch & Prof#=GALFRDSITLNGTN,Main            , 4
Up Type= 0
Dn Type= 3
Dn Slope=0.01322
Boundary for River Rch & Prof#=GALFRDSITLNGTN,Main            , 5
Up Type= 0
Dn Type= 3
Dn Slope=0.01322
Boundary for River Rch & Prof#=GALFRDSITLNGTN,Main            , 6
Up Type= 0
Dn Type= 3
Dn Slope=0.01322
DSS Import GetInterval= 0
DSS Import GetPeak= 0
DSS Import FillOption= 0

--- SITLNGTNCK.g01 (geometry) ---

Geom Title=Geometry
Program Version=6.10

River Reach=GALFRDSITLNGTN  ,Main
Reach XY= 30
2296625.24797946491737.666741308     2295883.783      493108.781
     2294677.557      493593.509      2294490.04      494192.823
     2294079.763      494537.247     2293509.976      495572.041
     2293530.217      496414.371     2292414.761      496669.121
     2292214.138      496985.862     2291847.884      496743.548
       2291502.6      496845.692     2290824.957       497512.99
     2289823.221      497942.308     2289955.353      498189.622
     2289824.127      499640.386     2289078.332      499703.769
     2287152.064      498852.654     2286564.601      499051.548
     2285528.785      498182.402     2283700.912      498421.847
     2282190.431       497524.22     2281952.713      497732.767
     2282350.696      498265.038      2282124.54      498718.696
     2281106.137      499289.448     2279798.972      499402.902
     2279156.163      499034.089     2278265.663      496710.111
     2277942.094      496575.703     2276760.021      496762.769

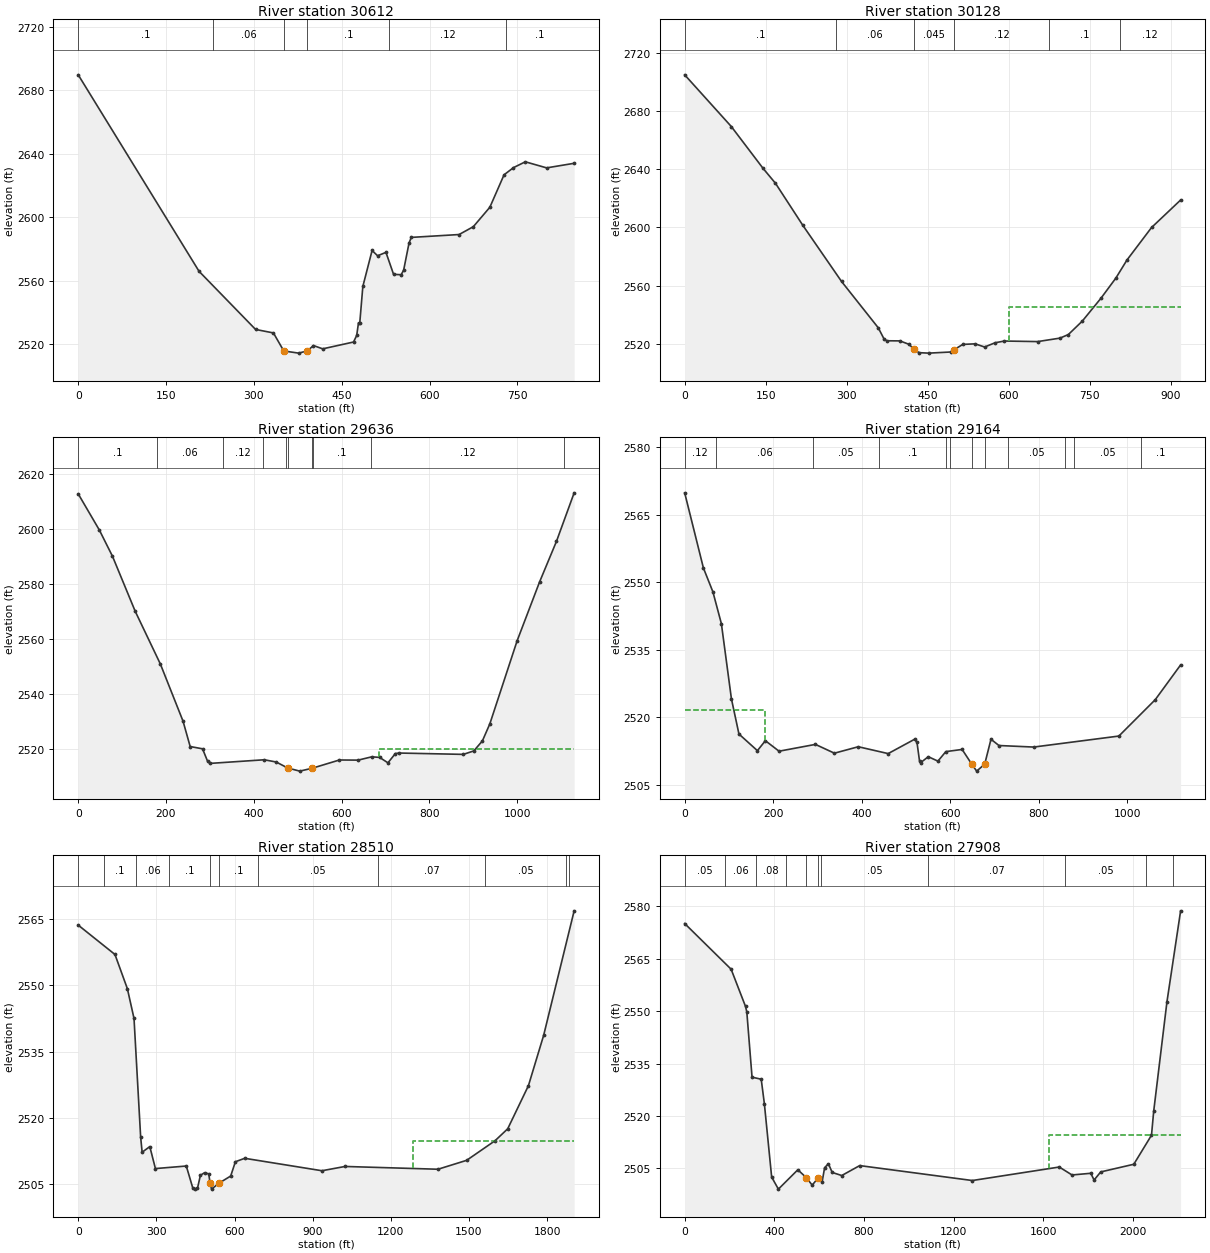
Type RM Length L Ch R = 1 ,30612   ,483.3,484.1,484.1
XS GIS Cut Line= 4
2296346.99048354491499.3293536552296735.33771585491831.962494566
 2296761.9989848  491896.51639342296799.15611267 492159.69261564
#Sta/Elev= 30
       0 2689.73   206.4 2566.04   302.9 2529.46   333.4 2527.26   351.1 2515.91
   376.6 2514.55   391.3 2515.99   401.8 2519.31   417.6 2517.25   470.2 2521.54
   475.6 2525.66   478.7 2533.64   480.8 2533.28   486.1 2556.51   501.9 2579.16
   511.3 2575.85   525.6 2577.97   538.6 2564.13   551.6 2563.91   555.8 2566.79
     565 2583.84   568.9  2587.4   650.5  2589.2   674.8 2594.14     703 2606.36
   727.3 2626.81   743.4 2631.32   763.6 2634.98     800 2631.16     847 2634.04
#Mann= 6 ,-1,0
       0      .1       0     230     .06       0   351.1    .045       0
   391.3      .1       0  531.33     .12       0  731.17      .1       0
Bank Sta=351.1,391.3
XS Rating Curve= 0 ,0
Exp/Cntr=0.3,0.1

Type RM Length L Ch R = 1 ,30128   ,508,492.1,470.8
XS GIS Cut Line= 3
2296035.50077866491789.6168342812296238.17851196492044.169228735
     2296697.064      492419.985
#Sta/Elev= 30
       0 2704.92    86.4 2669.36   145.3 2640.55   168.2 2630.35   218.8 2601.47
   290.5 2562.89   358.5 2531.04   369.3  2523.3   374.5 2522.11   398.6 2522.03
   415.9 2519.62   424.2 2516.29   434.3 2513.93   452.1 2513.62   492.4 2514.39
   498.6 2515.88   515.1 2519.62   537.9 2520.01   555.5 2517.83   574.8 2520.73
   592.1 2521.94   653.7 2521.55   695.1 2523.94   710.6  2526.4   736.4 2535.63
   770.9 2551.32   798.5 2565.17   819.1 2577.61   864.7 2599.98   918.5 2618.87
#Mann= 6 ,-1,0
       0      .1       0     280     .06       0   424.2    .045       0
   498.6     .12       0  675.38      .1       0  805.38     .12       0
#XS Ineff= 2 , 0
                             600         2545.54
Permanent Ineff=
       F       F
Bank Sta=424.2,498.6
XS Rating Curve= 0 ,0
Exp/Cntr=0.3,0.1

Type RM Length L Ch R = 1 ,29636   ,460.7,472.2,484.2
XS GIS Cut Line= 4
2295704.74846814492216.2482118582296045.74633391492531.138492279
2296154.49030455492561.0531542992296525.70651711492971.031597119
#Sta/Elev= 30
       0 2612.72    48.2 2599.56      78 2590.06   129.9 2570.01   187.1 2550.88
   238.8 2530.08   255.1 2520.84   283.3    2520   294.6 2515.54   300.3  2514.7
   423.9 2516.02   451.1 2515.21477.29022513.033   504.8 2511.89   532.9 2512.93
   595.2 2515.94   637.7 2515.89   668.8 2517.09   686.7 2516.89   705.7 2514.91
   722.6 2518.27   731.1 2518.47   877.4 2517.98   901.3 2519.24   920.9 2522.87
   937.9 2529.09  1000.2 2559.35  1051.1 2580.64  1089.7 2595.45    1130  2613.1
#Mann= 10 ,-1,0
       0      .1       0     180     .06       0     330     .12       0
     420      .1       0  474.15     .12       0477.2902    .045       0
   532.9     .12       0  534.15      .1       0  666.93     .12       0
 1106.93      .1       0
#XS Ineff= 2 , 0
                          684.42         2520.01
Permanent Ineff=
       F       F
Bank Sta=477.2902,532.9
XS Rating Curve= 0 ,0
Exp/Cntr=0.3,0.1

Type RM Length L Ch R = 1 ,29164   ,651.6,653.4,654.9
XS GIS Cut Line= 2
2295472.69097695492539.551090018 2296307.3885659493286.960042214
#Sta/Elev= 30
       0 2569.83    42.3 2553.16    63.7 2547.88    82.9 2540.81   105.6 2524.13
   122.6 2516.32   164.3 2512.63   182.3 2514.84   213.2 2512.51   295.4 2514.02
   338.2 2512.07   392.2  2513.5   459.7 2511.98   519.2 2515.15   524.8 2514.47
   530.5 2510.37   533.3 2509.98   550.3 2511.29   572.1 2510.31     590 2512.42
   626.8  2512.9     649 2509.57   659.7 2508.09   677.8 2509.64     692 2515.16
     710 2513.77   788.6 2513.43   980.9 2515.87  1063.1 2523.94  1120.4 2531.65
#Mann= 12 ,-1,0
       0     .12       0      70     .06       0     290     .05       0
     440      .1       0     590     .08       0     600      .1       0
     649    .045       0   677.8      .1       0     730     .05       0
     860      .1       0     880     .05       0    1030      .1       0
#XS Ineff= 2 , 0
          182.54 2521.55
Permanent Ineff=
       F       F
Bank Sta=649,677.8
XS Rating Curve= 0 ,0
Exp/Cntr(USF)=0,0
Exp/Cntr=0.3,0.1

Type RM Length L Ch R = 1 ,28510   ,601.5,602.6,592.5
XS GIS Cut Line= 3
 2295061.7069789492865.0649645762296094.62251381494010.728321957
2296440.14003429494116.202091366
#Sta/Elev= 30
       0 2563.68   141.1 2557.02   188.7 2549.26   214.2 2542.52   239.7  2515.6
   245.4 2512.18   274.8 2513.45   296.4 2508.47   414.9 2509.05   439.8 2504.07
   446.5 2503.86   457.7 2503.96   469.1 2506.95   484.9 2507.53     501 2507.27
   506.4 2505.14   511.8 2503.81   539.9 2505.14   585.3 2506.78   603.4 2510.02
   639.1  2510.8   935.6 2507.98  1024.3 2508.95  1381.1 2508.32  1491.1 2510.34
  1600.2 2514.79  1648.7 2517.49  1728.2 2527.26  1786.7 2538.68  1903.8 2566.92
#Mann= 11 ,-1,0
       0     .05       0     100      .1       0     220     .06       0
     350      .1       0   506.4    .045       0   539.9      .1       0
     690     .05       0    1150     .07       0 1562.55     .05       0
 1872.55      .1       0 1882.55     .12       0
#XS Ineff= 2 , 0
                         1284.51         2514.69
Permanent Ineff=
       F       F
Bank Sta=506.4,539.9
XS Rating Curve= 0 ,0
Exp/Cntr(USF)=0,0
Exp/Cntr=0.3,0.1

Type RM Length L Ch R = 1 ,27908   ,297,285.1,235.2
XS GIS Cut Line= 3
2294518.03788445 493096.977048242295064.60274506493676.895569185
2295890.03842888494826.746489775
#Sta/Elev= 30
       0 2575.05   207.2 2561.98   271.4 2551.34   277.2 2549.74   300.5 2531.11
   341.4 2530.53   355.4 2523.58     388 2502.54     418  2499.1   504.7 2504.63
   542.1 2502.42   568.8 2500.24595.08892502.278   612.9 2501.09   624.2 2505.23
   641.2 2506.35   658.1 2503.87   700.6 2502.99   780.8 2505.83  1283.2 2501.56
    1671 2505.42  1727.9 2503.15  1811.5 2503.63  1826.3 2501.71  1855.9 2504.02
  2003.4 2506.21  2082.4 2514.51  2092.2 2521.37  2151.3 2552.65  2212.3 2578.68
#Mann= 11 ,-1,0
       0     .05       0     180     .06       0     320     .08       0
     450     .05       0   542.1    .045       0595.0889      .1       0
     610     .05       0 1086.89     .07       0 1696.89     .05       0
 2056.89     .07       0 2176.89     .05       0
#XS Ineff= 2 , 0
                         1626.76         2514.67
Permanent Ineff=
       F       F
Bank Sta=542.1,595.0889
XS Rating Curve= 0 ,0
Exp/Cntr=0.3,0.1

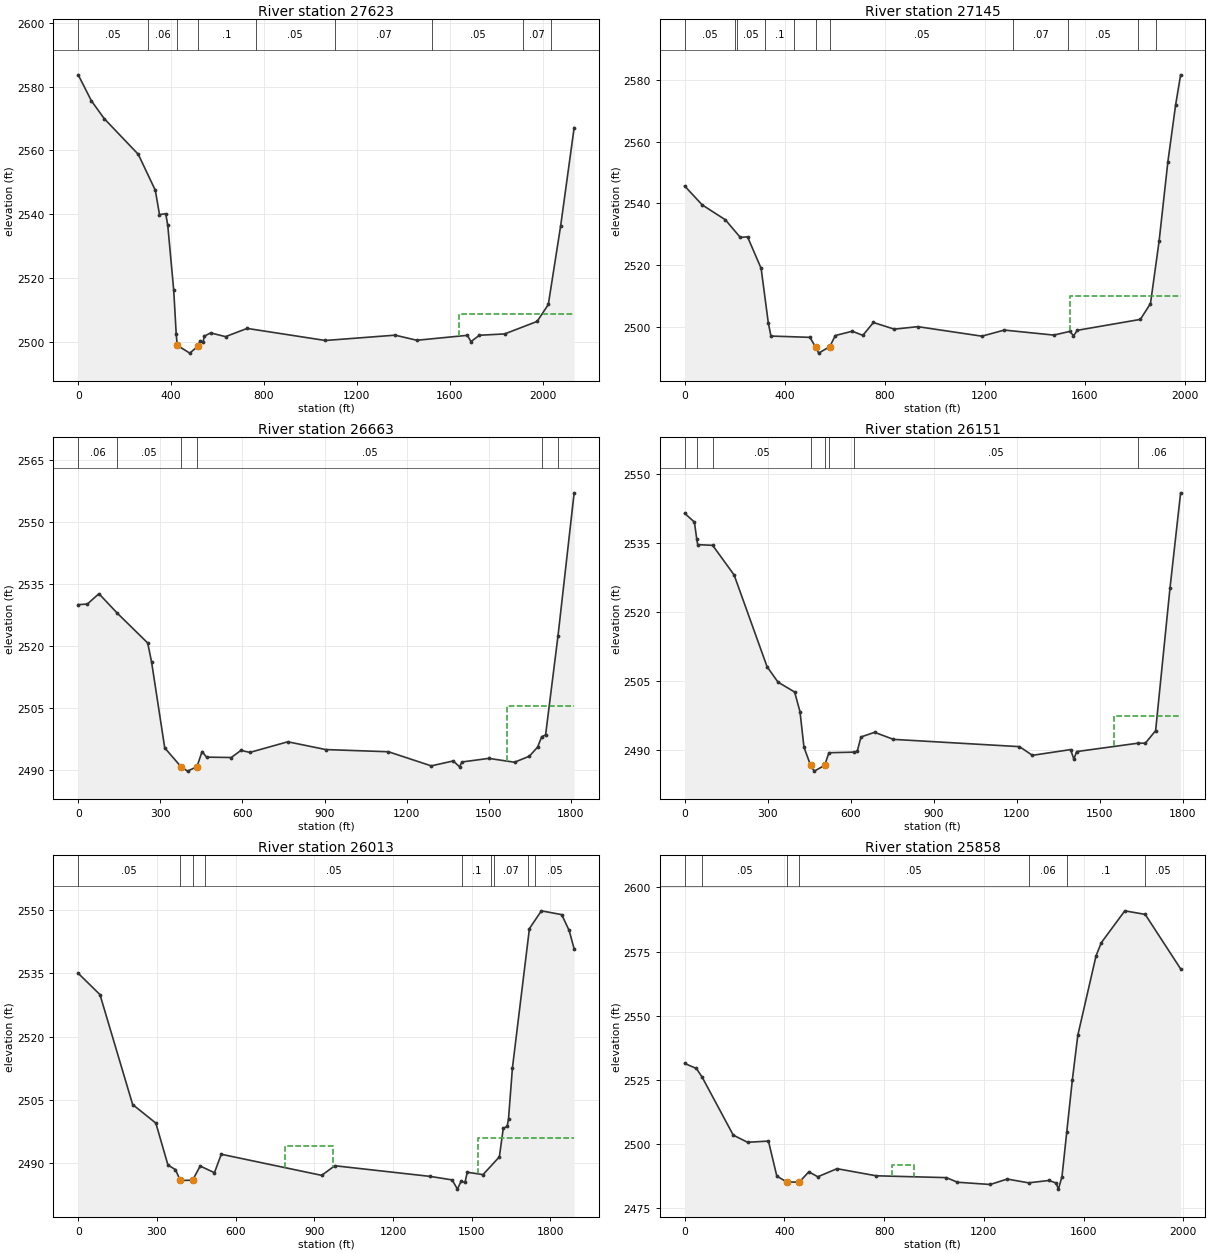
Type RM Length L Ch R = 1 ,27623   ,481.4,477.5,458.3
XS GIS Cut Line= 4
 2294278.6702395493410.2732031832294566.38351646493572.065760501
2294819.28393308493701.7887097342295786.95648398494876.188224648
#Sta/Elev= 30
       0 2583.74    56.8 2575.58  111.86    2570  258.71 2558.78   332.1 2547.48
  350.05 2539.88  377.05 2540.11  385.73 2536.46   411.4 2516.09  422.01  2502.4
   426.5 2498.81  480.45 2496.36   516.62498.592  525.41 2500.26  537.27 2499.77
  543.39 2501.68  569.95 2502.71  634.59 2501.54  727.55 2504.12 1064.44 2500.33
 1364.69    2502 1458.46  2500.4 1676.03 2501.95 1691.58 2499.98 1727.86 2501.97
  1836.7 2502.39 1976.64 2506.32 2024.72 2511.63 2077.92 2536.33 2136.03 2567.16
#Mann= 9 ,-1,0
       0     .05       0     300     .06       0   426.5    .045       0
   516.6      .1       0  764.31     .05       0 1104.31     .07       0
 1524.31     .05       0 1914.31     .07       0 2034.31     .05       0
#XS Ineff= 2 , 0
                         1639.86         2508.74
Permanent Ineff=
       F       F
Bank Sta=426.5,516.6
XS Rating Curve= 0 ,0
Exp/Cntr=0.3,0.1

Type RM Length L Ch R = 1 ,27145   ,465.5,481.8,505.3
XS GIS Cut Line= 4
2294078.30929966493798.1102077222294417.35146431494027.003777827
2294752.94167286494142.4054399592295595.47749731495023.566542809
#Sta/Elev= 30
       0 2545.64   69.82 2539.53  162.76 2534.68  222.52 2528.95  251.33 2529.16
  305.73 2518.91  334.33 2501.28  344.91 2496.96  500.89 2496.54 523.4182493.391
  535.76 2491.42 580.0672493.532  602.41 2497.13  670.08 2498.53  712.38 2497.18
  754.68 2501.36  838.09  2499.2  932.29 2500.01 1188.39 2496.92 1277.97  2498.9
 1476.18 2497.27 1540.56 2498.49  1554.7 2497.03 1570.26 2498.83 1822.04 2502.36
 1862.56 2507.49 1897.03 2527.72 1932.01  2553.4 1963.19 2571.99  1983.1 2581.71
#Mann= 11 ,-1,0
       0     .05       0     200     .06       0     210     .05       0
     320      .1       0  439.07     .05       0 523.418    .045       0
 580.067     .05       0 1313.95     .07       0 1533.95     .05       0
 1813.95     .07       0 1883.95      .1       0
#XS Ineff= 2 , 0
                         1539.17         2510.06
Permanent Ineff=
       F       F
Bank Sta=523.418,580.067
XS Rating Curve= 0 ,0
Exp/Cntr=0.3,0.1

Type RM Length L Ch R = 1 ,26663   ,512.5,512.1,490.2
XS GIS Cut Line= 3
 2293946.8377605494135.4060964782294147.17279235494335.541150121
2295211.89395564495433.127727311
#Sta/Elev= 30
       0 2529.94    33.3 2530.08    75.7 2532.58   143.2 2527.85   253.9 2520.68
   268.1 2516.09   316.2 2495.33  375.47  2490.8   399.5 2489.72     434  2490.8
   452.6 2494.45   468.9  2493.1   559.4 2493.01   594.8 2494.74   627.3 2494.24
   765.9 2496.81   904.5 2494.93  1133.7  2494.4    1290 2490.99  1370.4 2492.18
  1393.4 2490.77  1402.4 2491.93  1500.3  2492.8  1594.4 2491.87  1648.5 2493.32
  1678.7 2495.52  1693.8 2498.04  1707.9 2498.46  1753.2 2522.36  1812.3 2556.95
#Mann= 6 ,-1,0
       0     .06       0   143.2     .05       0  375.47    .045       0
     434     .05       0  1693.8     .06       0  1753.2     .07       0
#XS Ineff= 2 , 0
                         1566.82         2505.44
Permanent Ineff=
       F       F
Bank Sta=375.47,434
XS Rating Curve= 0 ,0
Exp/Cntr=0.3,0.1

Type RM Length L Ch R = 1 ,26151   ,126.4,138.8,149.9
XS GIS Cut Line= 2
2293625.87831328494542.3255993222295083.73447696495583.455222473
#Sta/Elev= 30
       0 2541.45    35.2 2539.54    43.8 2535.77    47.1 2534.65   101.1  2534.5
   178.6 2528.07   297.7 2508.16   337.1 2504.83   397.2 2502.68   416.6 2498.41
   430.9 2490.72     455 2486.75   468.2 2485.52505.39952486.768   521.1 2489.51
   611.6 2489.64   623.1 2489.78   636.9 2492.93     686 2493.94   754.2 2492.41
  1209.4 2490.83  1256.2 2488.95  1393.9 2490.19  1405.9 2488.13  1415.9 2489.76
  1636.1 2491.57  1664.2 2491.59  1701.2  2494.3  1753.1 2525.22  1791.5 2545.89
#Mann= 8 ,-1,0
       0     .05       0    43.8     .06       0   101.1     .05       0
     455    .045       0505.3995     .05       0   521.1      .1       0
   611.6     .05       0  1636.1     .06       0
#XS Ineff= 2 , 0
                         1551.46          2497.5
Permanent Ineff=
       F       F
Bank Sta=455,505.3995
XS Rating Curve= 0 ,0
Exp/Cntr=0.3,0.1

Type RM Length L Ch R = 1 ,26013   ,152.6,154.7,158
XS GIS Cut Line= 4
2293665.08879086494639.9339118842293821.48093171494770.866867013
2294723.46351149495989.2707550212294890.76673193496022.003993804
#Sta/Elev= 30
       0 2534.97    82.9 2529.92   207.5 2503.92   295.9 2499.53     342 2489.62
   370.6 2488.52   389.22485.965  435.95 2486.02   464.9 2489.37   519.3  2487.8
   545.3 2492.16   927.8 2487.17   978.2 2489.44  1341.6 2486.92  1425.3 2486.09
  1445.5 2483.91  1458.9 2485.72  1474.4 2485.53    1483 2487.91    1543 2487.34
  1605.3 2491.54  1620.2 2498.28  1635.2 2498.77  1640.2 2500.52  1655.1 2512.57
  1719.9 2545.54  1765.5 2549.74  1842.9 2548.84  1871.4 2545.09  1890.4 2540.73
#Mann= 9 ,-1,0
       0     .05       0   389.2    .045       0  435.95      .1       0
  483.97     .05       0 1463.97      .1       0 1573.97     .06       0
 1583.97     .07       0 1713.97      .1       0 1739.91     .05       0
#XS Ineff= 2 ,-1
  789.55  970.81 2494.03 1523.81  1890.4 2496.08
Permanent Ineff=
       F       F
Bank Sta=389.2,435.95
XS Rating Curve= 0 ,0
Exp/Cntr(USF)=0,0
Exp/Cntr=0.3,0.1

Type RM Length L Ch R = 1 ,25858   ,267.2,265.1,264.8
BEGIN DESCRIPTION:
structure xs 4
END DESCRIPTION:
XS GIS Cut Line= 3
2293614.17041942494698.1263363852294476.14570735496018.366967272
2294879.85565233496102.018577494
#Sta/Elev= 30
       0 2531.39      47 2529.44    70.1 2526.05   194.7 2503.47   252.1 2500.66
     336 2501.13   369.5  2487.5   409.7 2485.16  459.84 2485.15   497.9 2489.15
   533.9 2487.22     611 2490.37     768  2487.6  1049.6 2486.88  1093.9 2485.09
  1225.6 2484.21  1293.5 2486.33  1379.4 2484.85  1460.6 2485.77  1489.3 2484.81
  1498.9  2482.4  1513.2 2487.25  1532.5 2504.79  1554.8 2525.01  1576.7 2542.38
  1649.7 2573.29  1670.7 2578.44  1765.2 2590.89  1846.9  2589.5    1989 2568.27
#Mann= 7 ,-1,0
       0     .06       0    70.1     .05       0   409.7    .045       0
  459.84     .05       0  1379.4     .06       0  1532.5      .1       0
  1846.9     .05       0
#XS Ineff= 1 ,-1
  832.57  921.662491.689
Permanent Ineff=
       F
Bank Sta=409.7,459.84
XS Rating Curve= 0 ,0
Exp/Cntr(USF)=0,0
Exp/Cntr=0.5,0.3

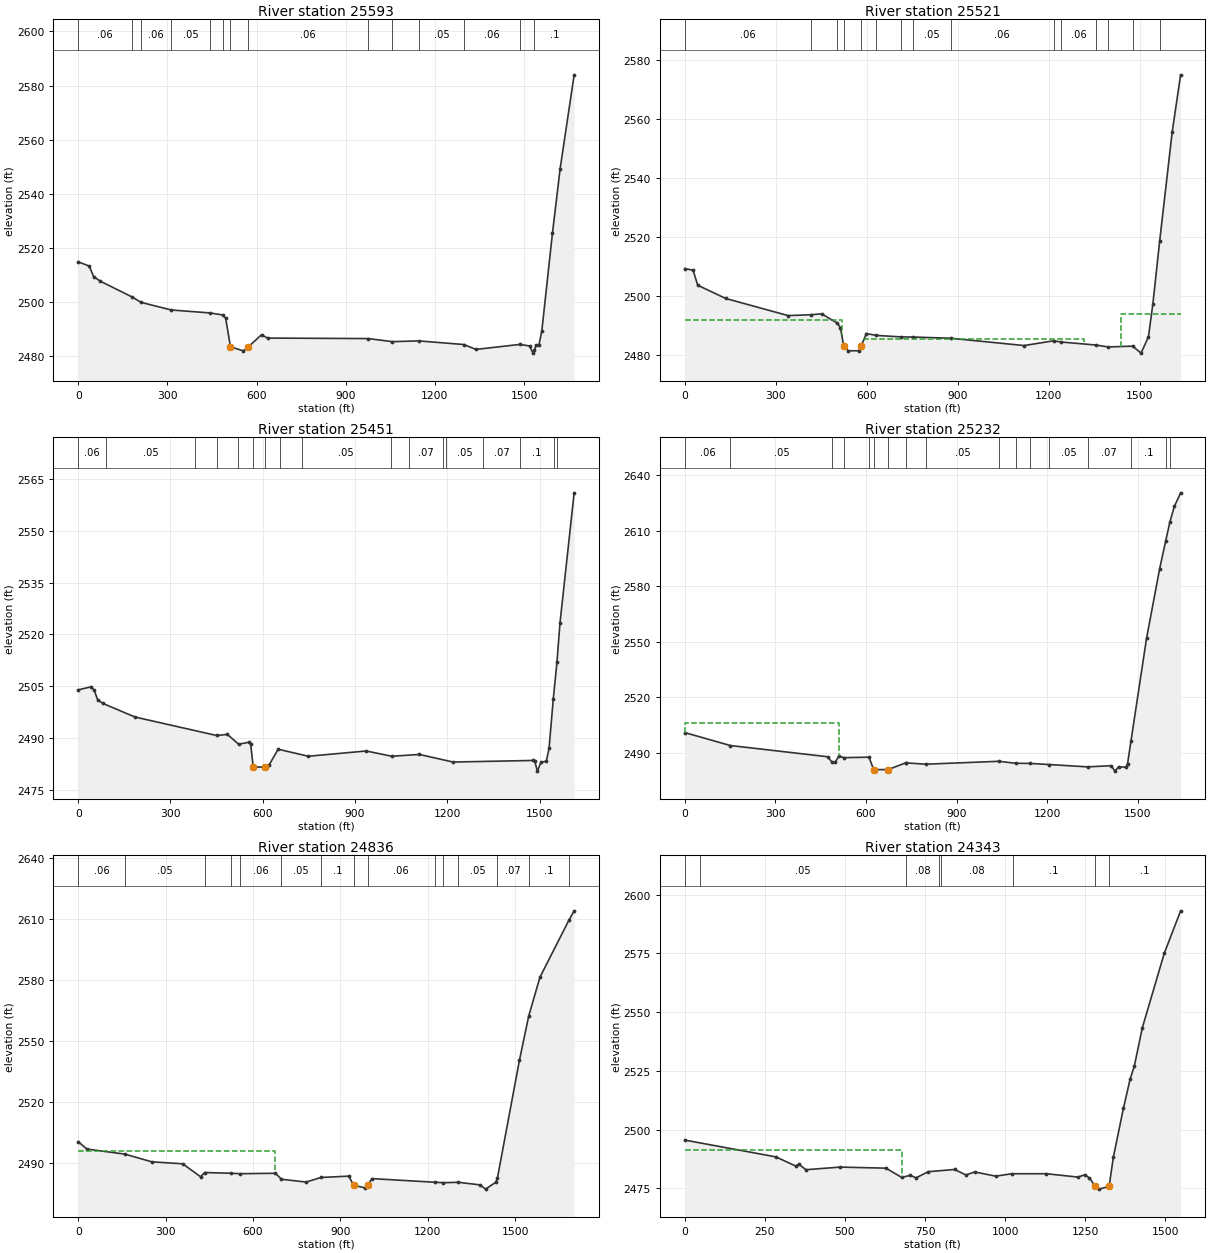
Type RM Length L Ch R = 1 ,25593   ,75.3,71.8,72.2
BEGIN DESCRIPTION:
structure xs 3
END DESCRIPTION:
XS GIS Cut Line= 3
2293367.71694098494839.468568108  2293836.557395495468.875856405
2294353.54015952496185.536457465
#Sta/Elev= 30
       0 2514.92      37 2513.37      52 2509.48    74.4 2507.78   181.6 2501.94
   211.6 2499.96   313.1 2497.15   444.6 2496.05   487.5 2495.29   496.3 2494.04
   512.12483.581   555.8 2482.03   570.4 2483.34   616.8 2488.02   636.9 2486.78
   975.6 2486.59  1056.5 2485.46  1146.5 2485.73  1297.7 2484.39  1337.8 2482.59
  1485.6 2484.43  1518.3 2483.87    1530 2481.22  1534.9 2482.29  1539.8 2484.12
  1549.8  2484.1  1559.6  2489.3  1595.6  2525.6  1621.4 2549.36  1668.5 2583.98
#Mann= 14 ,-1,0
       0     .06       0   181.6     .05       0   211.6     .06       0
   313.1     .05       0   444.6     .07       0   487.5     .05       0
   512.1    .045       0   570.4     .06       0   975.6     .05       0
  1056.5     .06       0  1146.5     .05       0  1297.7     .06       0
  1485.6     .07       0  1534.9      .1       0
#XS Ineff= 2 ,-1
       0   490.1 2492.41   592.4 1201.34 2484.02
Permanent Ineff=
       F       F
Bank Sta=512.1,570.4
XS Rating Curve= 0 ,0
Exp/Cntr(USF)=0,0
Exp/Cntr=0.5,0.3

Type RM Length L Ch R = 1 ,25521   ,77.2,70.1,58.6
BEGIN DESCRIPTION:
structure xs 2
END DESCRIPTION:
XS GIS Cut Line= 3
2293306.53033374494903.5918154282293821.37080307495549.018642874
2294285.52785642496212.053664198
#Sta/Elev= 30
       0 2509.37    27.6 2508.82      43 2503.72   135.1 2499.24     341 2493.43
   416.5 2493.72   451.7 2494.02     503  2490.9   513.7 2489.32   523.9 2483.24
   539.3 2481.49   574.4 2481.52     5822483.127   599.2 2487.35   631.4 2486.72
   713.3 2486.21   753.1 2486.16   876.6 2485.76  1118.8 2483.28  1216.4 2484.89
  1240.8 2484.48  1356.2 2483.45  1396.4  2482.8  1476.8 2483.08  1504.5 2480.71
  1528.9 2486.22  1543.6 2497.45  1565.9 2518.64    1607 2555.48    1635 2575.02
#Mann= 15 ,-1,0
       0     .06       0   416.5     .07       0     503     .06       0
   523.9    .045       0     582     .06       0   631.4      .1       0
   713.3     .06       0   753.1     .05       0   876.6     .06       0
  1216.4     .05       0  1240.8     .06       0  1356.2     .07       0
  1396.4     .06       0  1476.8     .07       0  1565.9      .1       0
#XS Ineff= 3 ,-1
       0   517.9    2492  590.21  1317.3 2485.41 1438.95 1685.39 2493.91
Permanent Ineff=
       F       F       F
Bank Sta=523.9,582
XS Rating Curve= 0 ,0
Exp/Cntr(USF)=0,0
Exp/Cntr=0.5,0.3

Type RM Length L Ch R = 1 ,25451   ,217,218.8,226.1
XS GIS Cut Line= 4
2293195.91236831494963.6292731752293574.16312757495360.065165095
2293643.26663167495414.6205630652294181.54655831496229.314506092
#Sta/Elev= 30
       0 2503.95    40.9 2504.81    51.9 2503.88      63  2501.1    80.5 2500.01
   184.6 2496.08     450 2490.73   485.1 2491.04   521.8 2488.19   555.9  2488.8
   560.7 2488.17   569.1 2481.59   606.6 2481.59   621.4 2482.31     650 2486.75
   748.2 2484.72   936.3 2486.24  1019.5 2484.72  1109.3 2485.24  1218.7 2483.04
  1478.6  2483.5  1484.3 2483.23    1493 2480.41  1504.5 2483.03  1521.9 2483.24
  1530.8    2487  1544.6 2501.37  1556.5 2511.93  1566.4 2523.35  1612.4 2561.01
#Mann= 17 ,-1,0
       0     .06       0      90     .05       0     380     .06       0
     450     .05       0     520     .06       0   569.1    .045       0
   606.6     .05       0  655.98      .1       0  725.98     .05       0
 1015.98     .06       0 1075.98     .07       0 1185.98     .06       0
 1195.98     .05       0 1315.98     .07       0 1435.98      .1       0
 1545.98     .07       0 1555.98      .1       0
Bank Sta=569.1,606.6
XS Rating Curve= 0 ,0
Exp/Cntr(USF)=0,0
Exp/Cntr=0.3,0.1

Type RM Length L Ch R = 1 ,25232   ,416,396,357.1
XS GIS Cut Line= 3
2293021.42450951495160.4284088812293659.54434921495708.738789655
2294116.46966652496365.765883858
#Sta/Elev= 30
       0 2500.99   151.3 2493.99     473 2487.93   488.8 2484.85   498.3 2484.96
   510.2  2488.3   527.2 2487.44   610.1  2487.7  625.57    2481   673.4    2481
   731.5 2484.63   731.5 2484.62     799 2483.92  1040.4 2485.48  1095.2 2484.42
  1143.8 2484.31  1206.7 2483.73  1333.5 2482.47  1411.9  2483.1  1423.9 2480.17
  1436.3 2482.47  1460.6 2482.33    1466 2484.19  1477.2 2496.33  1528.8 2551.84
    1572 2589.26  1592.5 2604.62  1606.1 2614.62  1620.9 2623.03  1641.6 2630.38
#Mann= 17 ,-1,0
       0     .06       0   151.3     .05       0   488.8     .06       0
   527.2     .05       0   610.1     .06       0  625.57    .045       0
   673.4     .05       0   731.5      .1       0     799     .05       0
  1040.4     .06       0  1095.2     .07       0  1143.8     .06       0
  1206.7     .05       0  1333.5     .07       0  1477.2      .1       0
  1592.5     .07       0  1606.1      .1       0
#XS Ineff= 2 , 0
          512.11 2506.33
Permanent Ineff=
       F       F
Bank Sta=625.57,673.4
XS Rating Curve= 0 ,0
Exp/Cntr(USF)=0,0
Exp/Cntr=0.3,0.1

Type RM Length L Ch R = 1 ,24836   ,448.5,492.7,522.5
XS GIS Cut Line= 4
2292954.74617311495197.9518560392293365.58903999495965.049932719
2293539.50283864495969.9543750862293885.90025377 496530.12945911
#Sta/Elev= 30
       0 2500.37      30 2496.75   160.1 2494.28   253.2 2490.47   358.9 2489.52
   420.1 2483.15   434.3 2485.23   525.5 2484.86   557.2 2484.65   677.2 2484.86
   697.9 2481.93   782.5 2480.54   833.8 2482.81   928.8 2483.45  946.22 2478.97
   984.8 2477.68   993.9 2479.16  1008.8 2482.24  1224.3 2480.45  1253.3 2480.23
  1305.6 2480.43  1380.1 2479.14  1398.6 2477.07  1433.5 2480.41  1439.3 2482.49
  1514.9 2540.37  1546.8 2562.14  1585.4 2581.23  1684.3 2609.08  1702.8 2613.83
#Mann= 15 ,-1,0
       0     .06       0   160.1     .05       0   434.3     .06       0
   525.5     .05       0   557.2     .06       0   697.9     .05       0
   833.8      .1       0  946.22    .045       0   993.9     .06       0
  1224.3     .07       0  1253.3     .06       0  1305.6     .05       0
  1439.3     .07       0  1546.8      .1       0  1684.3     .07       0
#XS Ineff= 2 , 0
          675.38 2495.98
Permanent Ineff=
       F       F
Bank Sta=946.22,993.9
XS Rating Curve= 0 ,0
Exp/Cntr(USF)=0,0
Exp/Cntr=0.3,0.1

Type RM Length L Ch R = 1 ,24343   ,227.7,227.8,228.2
XS GIS Cut Line= 3
2292923.13537846495258.2284222162293539.11895376 496504.03476573
2293657.81473779496607.565265354
#Sta/Elev= 30
       0 2495.59   284.4 2488.44   346.4 2484.54   355.8 2485.39   378.1 2482.98
   485.2 2484.09     628 2483.64   677.1  2479.7   703.9  2480.6   721.7 2479.52
   760.4 2482.14   842.2 2483.08   877.7 2480.72   904.7 2482.03   970.4 2480.24
  1020.7 2481.26  1127.8 2481.28  1227.2 2479.84  1247.8  2480.8    1263 2479.46
1281.2092475.879  1292.9 2474.721324.1992475.872  1337.5  2488.3  1368.7 2509.03
  1389.8 2521.54  1402.7 2526.96    1428 2543.44  1496.2 2574.98  1547.3  2593.1
#Mann= 8 ,-1,0
       0     .06       0    48.1     .05       0   691.1     .08       0
   794.2      .1       0   800.2     .08       0  1022.8      .1       0
1281.209    .045       01324.199      .1       0
#XS Ineff= 2 , 0
          678.76 2491.48
Permanent Ineff=
       F       F
Bank Sta=1281.209,1324.199
XS Rating Curve= 0 ,0
Exp/Cntr(USF)=0,0
Exp/Cntr=0.3,0.1

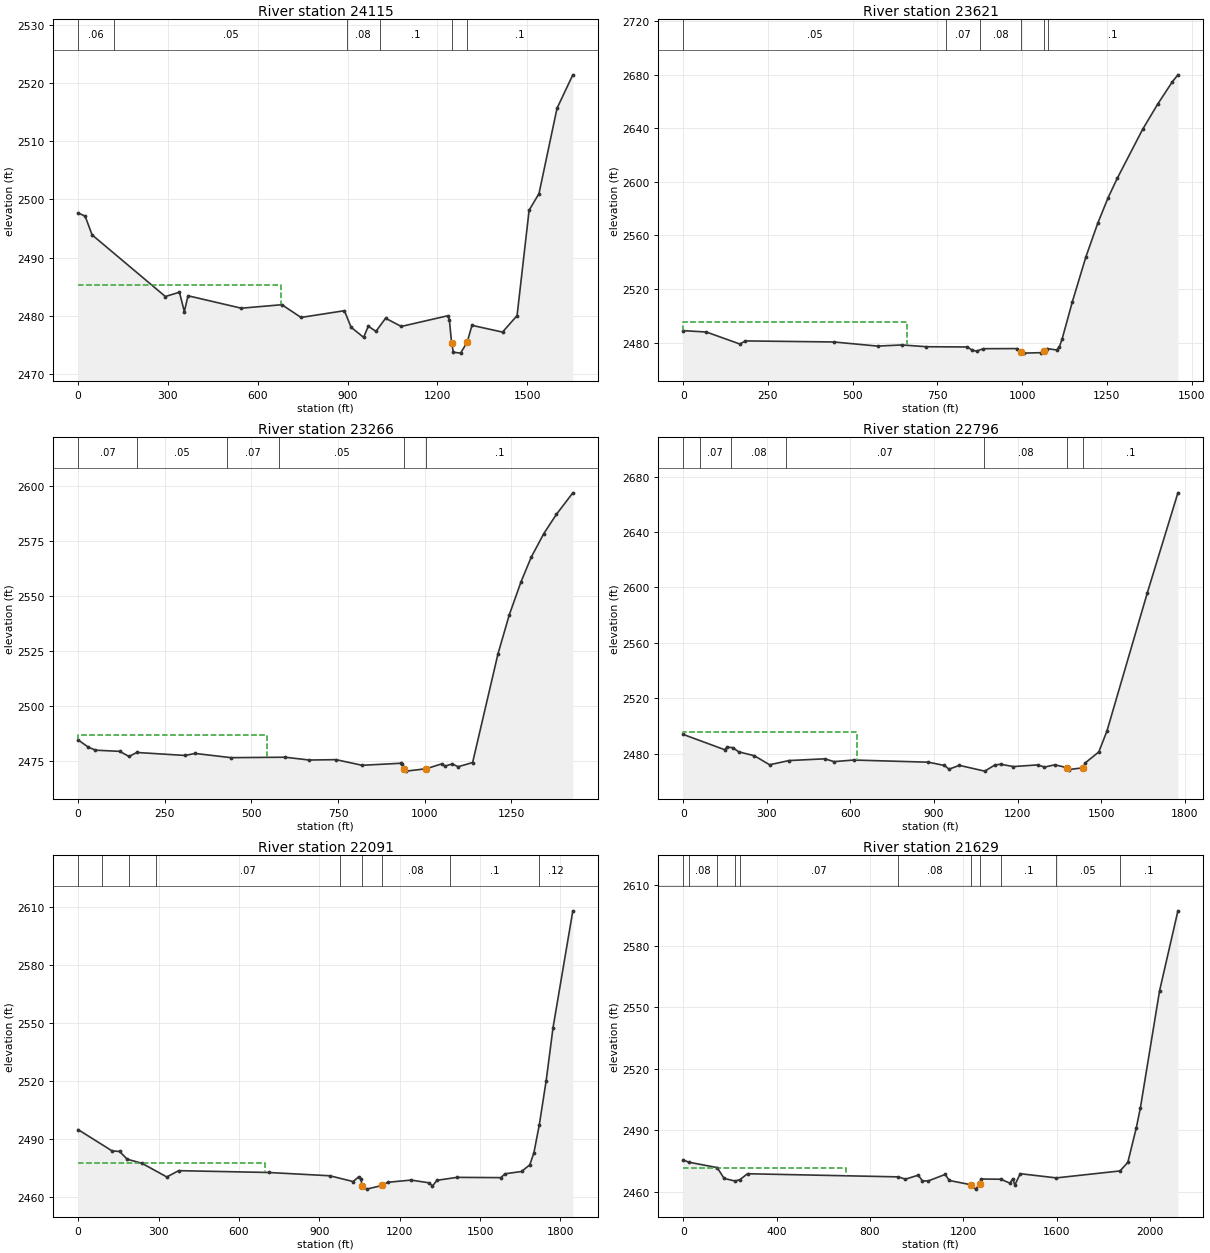
Type RM Length L Ch R = 1 ,24115   ,473.6,494.5,511.4
XS GIS Cut Line= 3
2292709.22554287495388.0341802592293121.02193701496161.777733837
 2293457.1463025496860.781213963
#Sta/Elev= 30
       0 2497.67    23.3 2497.13    46.6  2493.9   291.3  2483.3   338.3 2484.04
   354.7 2480.69   366.8 2483.43     545 2481.29   680.3 2481.89   744.4  2479.7
   889.2 2480.86   911.5 2478.02   953.3 2476.27     969  2478.2   994.5  2477.3
  1026.7 2479.56  1079.2 2478.15  1235.1    2480  1239.8  2479.31247.0522475.388
  1253.1 2473.72    1277 2473.561299.1522475.424  1315.2 2478.34  1417.3 2477.18
  1465.9 2480.02  1506.1 2498.15  1539.1 2501.01  1599.3 2515.68  1652.1 2521.44
#Mann= 6 ,-1,0
       0     .06       0     120     .05       0   896.5     .08       0
  1006.5      .1       01247.052    .045       01299.152      .1       0
#XS Ineff= 2 , 0
          677.41 2485.23
Permanent Ineff=
       F       F
Bank Sta=1247.052,1299.152
XS Rating Curve= 0 ,0
Exp/Cntr=0.3,0.1

Type RM Length L Ch R = 1 ,23621   ,364.3,355.3,337.2
XS GIS Cut Line= 4
2292688.97079151  495610.4816252 2292815.8952353496151.791010637
2292827.71368733496715.2899101432292970.20748354497023.810280365
#Sta/Elev= 30
       0 2488.86    68.1 2487.85   167.1 2478.88   183.5  2481.2   444.2 2480.41
   573.4 2477.34   645.4 2478.19   717.4 2476.86   837.4 2476.68   853.4 2474.23
   865.4 2473.59   885.5 2475.39   985.5 2475.47   996.5 2473.17  1005.5 2472.08
  1055.7 2472.44  1063.9 2473.37  1073.5 2475.47  1101.5 2474.44  1109.5  2476.6
    1118 2482.75  1148.1 2510.47    1188 2543.94    1223  2569.1  1253.5 2588.13
  1280.3  2602.5  1355.2  2639.1  1399.3 2657.81  1443.3 2674.82  1459.5  2679.9
#Mann= 6 ,-1,0
       0     .05       0  775.99     .07       0  875.99     .08       0
   996.5    .045       0  1063.9     .08       0 1075.99      .1       0
#XS Ineff= 2 , 0
          658.93 2495.54
Permanent Ineff=
       F       F
Bank Sta=996.5,1063.9
XS Rating Curve= 0 ,0
Exp/Cntr=0.3,0.1

Type RM Length L Ch R = 1 ,23266   ,457.8,469.8,453.4
XS GIS Cut Line= 4
2292562.96601531495716.1479364572292403.36588195496418.626490362
2292535.02012604496836.8703125232292724.87104427497026.857442682
#Sta/Elev= 30
       0 2484.62    29.8 2481.32      50 2479.98     120 2479.44   146.9 2477.12
   169.2 2478.94   308.7 2477.58   337.4  2478.5   441.1 2476.58   597.5 2476.78
   666.5 2475.51     744 2475.68   819.5 2473.12   930.4 2474.04   933.6 2473.73
   939.9 2471.35   946.3 2470.47    1004 2471.55  1050.1 2473.81  1058.5 2472.73
  1079.5 2473.75  1096.2 2472.47  1138.2 2474.36  1211.4 2523.67  1244.1 2541.44
    1278 2556.43  1307.6 2567.66  1343.7 2578.28  1379.8 2586.96  1427.4 2596.77
#Mann= 6 ,-1,0
       0     .07       0     170     .05       0     430     .07       0
     580     .05       0   939.9    .045       0    1004      .1       0
#XS Ineff= 2 , 0
          545.35 2486.73
Permanent Ineff=
       F       F
Bank Sta=939.9,1004
XS Rating Curve= 0 ,0
Exp/Cntr=0.3,0.1

Type RM Length L Ch R = 1 ,22796   ,704.7,705,701
XS GIS Cut Line= 3
2291869.90616591495624.9240424292292200.29877134496920.925899353
2292317.37619586497342.704826126
#Sta/Elev= 30
       0 2494.03   148.9 2482.99   157.1 2484.89   177.8 2484.47   199.4 2481.46
   255.4 2478.65   309.9 2472.15   379.5 2475.18     508 2476.44     541 2474.41
   611.2 2475.56   879.5 2474.01   937.3 2471.65   953.8 2468.98     991 2471.72
  1081.8 2467.56  1118.9 2472.05  1139.6  2472.5    1185 2470.84  1271.7 2472.06
  1296.4 2470.48  1333.6 2472.121376.5582470.074  1383.4 2468.691435.6582469.982
  1441.7 2473.33  1491.3 2481.42  1520.4  2496.4  1665.7 2596.34  1775.2 2668.27
#Mann= 7 ,-1,0
       0     .05       0      60     .07       0     170     .08       0
     370     .07       0    1080     .08       01376.558    .045       0
1435.658      .1       0
#XS Ineff= 2 , 0
           623.1 2495.85
Permanent Ineff=
       F       F
Bank Sta=1376.558,1435.658
XS Rating Curve= 0 ,0
Exp/Cntr(USF)=0,0
Exp/Cntr=0.3,0.1

Type RM Length L Ch R = 1 ,22091   ,471.3,461.3,445.5
XS GIS Cut Line= 4
2291595.48375653495694.5583643822291635.54341317496650.747656645
2291777.01885195497134.0668516732292077.31267933497375.803837683
#Sta/Elev= 30
       0 2494.94   126.7 2483.94   154.8 2483.65   182.8 2479.68   238.8 2477.49
   330.9 2470.47   374.9 2473.73   711.2 2472.79   939.4 2471.09  1026.2  2468.1
  1047.1 2470.59  1055.4  2469.5  1059.4 2466.05  1076.3 2464.19  1134.6 2466.09
  1155.5 2467.73  1242.5 2468.86  1309.7 2467.45  1322.2 2465.77  1338.8 2468.75
  1413.9 2470.27  1577.6 2470.13  1593.1 2472.12  1654.7  2473.3  1685.5 2476.75
  1700.9 2483.01  1721.1 2497.53  1746.7  2520.3  1772.3  2547.7  1846.1    2608
#Mann= 9 ,-1,0
       0      .1       0      90     .07       0     190     .08       0
     290     .07       0  977.03     .08       0  1059.4    .045       0
  1134.6     .08       0 1387.03      .1       0 1720.63     .12       0
#XS Ineff= 2 , 0
           698.8 2477.46
Permanent Ineff=
       F       F
Bank Sta=1059.4,1134.6
XS Rating Curve= 0 ,0
Exp/Cntr=0.3,0.1

Type RM Length L Ch R = 1 ,21629   ,501,501.5,486.1
XS GIS Cut Line= 3
2290791.29561128495964.7924951392291696.57832889497631.678297932
2291912.51198981497683.684106404
#Sta/Elev= 30
       0 2475.48    23.2 2474.39   145.5 2471.73     175 2466.44   222.2 2465.17
   242.8 2465.84   275.3 2468.73   921.3  2467.2   951.8 2466.07  1006.4 2468.03
  1024.5 2465.32  1047.4 2465.13  1121.9 2468.39  1139.6 2465.44  1233.9 2463.32
  1252.2 2461.21  1269.4  2463.6    1275 2466.16  1360.8 2466.05  1399.1 2464.12
  1411.5  2466.3  1420.6 2463.21  1443.4 2468.75  1598.1  2466.7  1870.9  2470.1
  1904.4 2474.27  1940.9 2491.25  1958.2 2500.91  2040.3 2558.07    2119 2597.22
#Mann= 11 ,-1,0
       0     .07       0    23.2     .08       0   145.5     .07       0
   222.2     .08       0   242.8     .07       0   921.3     .08       0
  1233.9    .045       0  1269.4     .08       0  1360.8      .1       0
  1598.1     .05       0  1870.9      .1       0
#XS Ineff= 2 , 0
          698.47  2471.6
Permanent Ineff=
       F       F
Bank Sta=1233.9,1269.4
XS Rating Curve= 0 ,0
Exp/Cntr=0.3,0.1