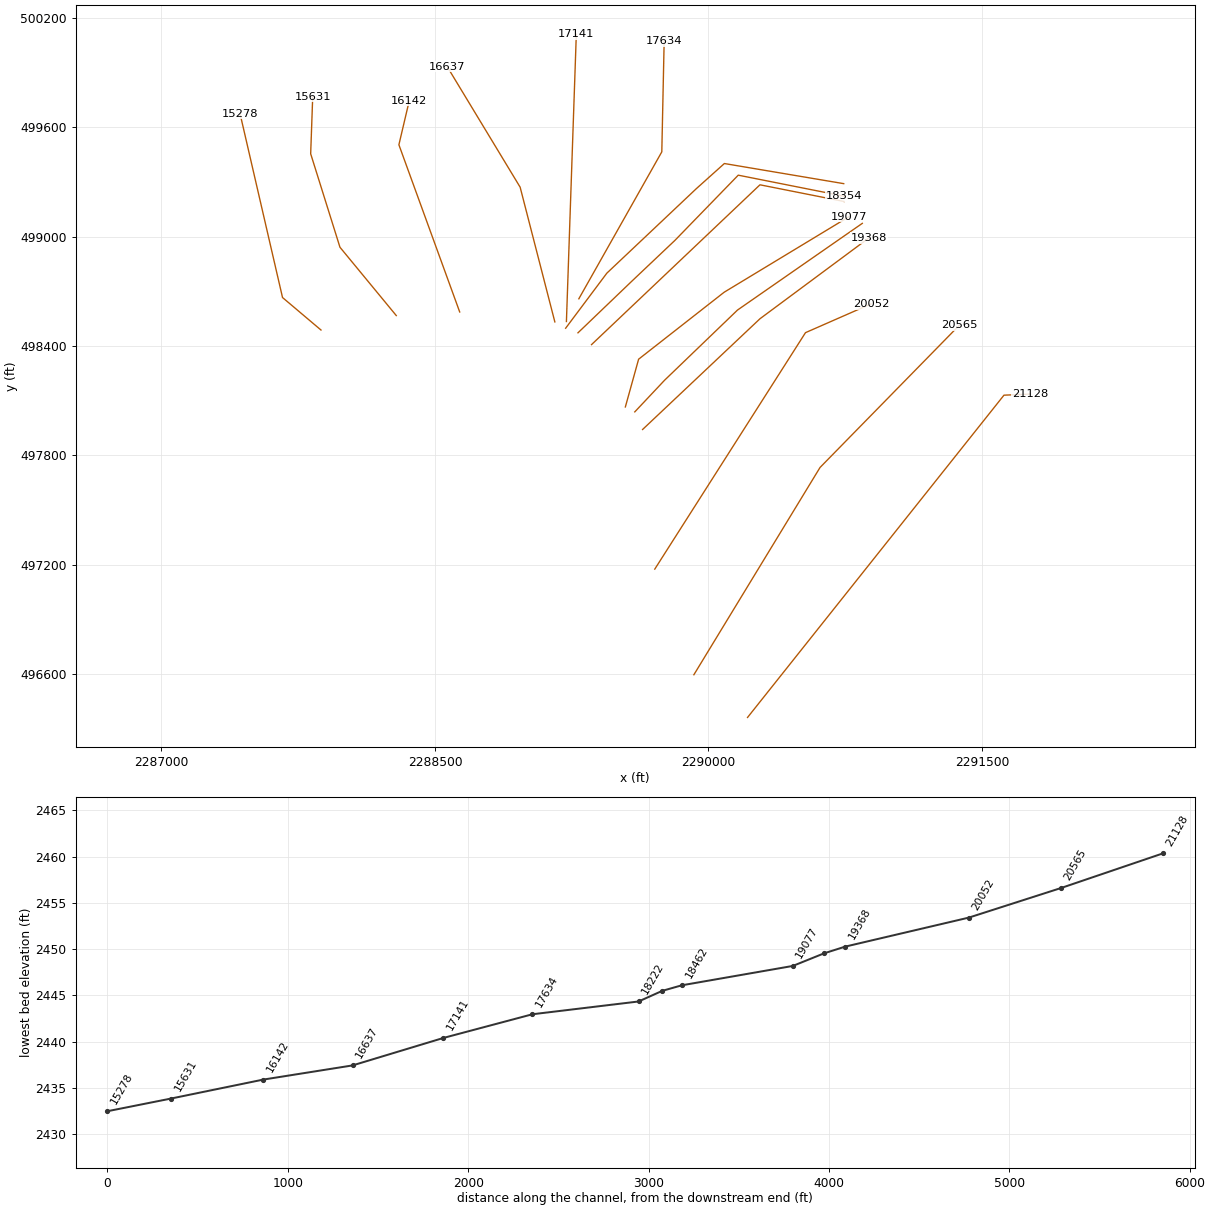
HEC-RAS study SITLNGTNCK.prj: SITLNGTNCK

--- SITLNGTNCK.g01 (geometry) --- (continued)

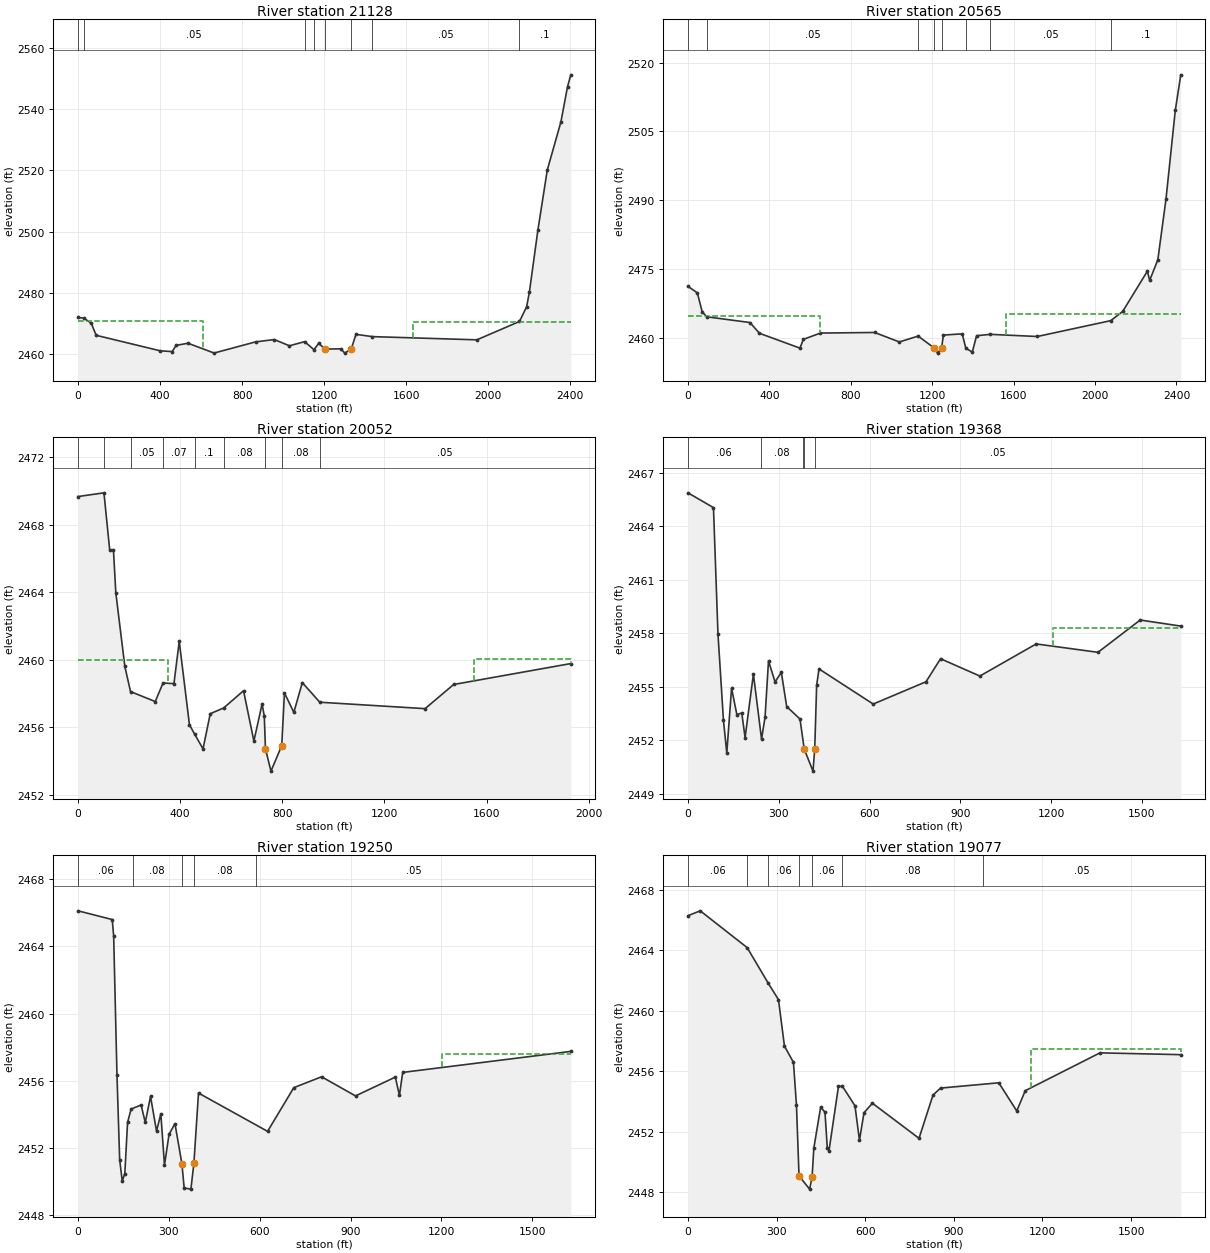
Type RM Length L Ch R = 1 ,21128   ,556.8,562.9,567.9
XS GIS Cut Line= 3
2290214.48332348496362.8650387472291620.98849499498130.646001862
 2291764.2854987 498136.24860604
#Sta/Elev= 30
       0 2472.03    28.5 2471.75    64.3 2470.13    88.3 2466.17     401  2461.1
   458.9 2460.86   478.2 2462.88     536 2463.58   663.3 2460.38   865.4 2464.02
   956.5 2464.78  1030.6 2462.75  1104.5  2464.1  1150.1 2461.48  1173.5 2463.56
  1204.1 2461.67  1280.9 2461.75  1300.5 2460.35    1332 2461.72    1355 2466.49
  1434.7 2465.74  1944.3 2464.69  2152.1 2470.68  2187.1  2475.5  2200.5  2480.3
  2241.8 2500.45  2287.7 2520.13  2354.3 2535.88  2386.3 2547.31  2402.5  2551.2
#Mann= 8 ,-1,0
       0     .07       0    28.5     .05       0  1104.5     .07       0
  1150.1     .08       0  1204.1    .045       0    1332      .1       0
  1434.7     .05       0  2152.1      .1       0
#XS Ineff= 2 , 0
          607.04 2470.68 1632.39         2470.43
Permanent Ineff=
       F       F
Bank Sta=1204.1,1332
XS Rating Curve= 0 ,0
Exp/Cntr=0.3,0.1

Type RM Length L Ch R = 1 ,20565   ,510.9,513,505.5
XS GIS Cut Line= 3
2289920.23982871 496597.255853862290612.18967975497734.113843108
2291375.07756525498513.008726429
#Sta/Elev= 30
       0 2471.19      46 2469.77    70.1 2465.57    93.6 2464.54   304.3  2463.3
   351.1 2460.95   550.1 2457.71   566.5 2459.62   650.8    2461   916.8 2461.13
  1038.5 2459.06  1130.8 2460.34  1207.8  2457.8  1226.8 2456.62  1245.8 2457.73
  1254.9 2460.56  1347.2 2460.83  1365.2 2457.67  1396.8 2456.86  1417.9 2460.42
  1485.2 2460.72  1715.9 2460.25    2077 2463.71  2135.8 2465.73  2256.9  2474.5
  2268.4 2472.51  2308.4 2477.01  2348.5 2490.26  2394.1  2509.6  2421.1 2517.37
#Mann= 8 ,-1,0
       0     .06       0    93.6     .05       0  1130.8     .08       0
  1207.8    .045       0  1245.8     .08       0  1365.2      .1       0
  1485.2     .05       0    2077      .1       0
#XS Ineff= 2 , 0
           650.7 2464.69 1562.98         2465.06
Permanent Ineff=
       F       F
Bank Sta=1207.8,1245.8
XS Rating Curve= 0 ,0
Exp/Cntr=0.3,0.1

Type RM Length L Ch R = 1 ,20052   ,682,684.2,651.2
XS GIS Cut Line= 3
2289705.69555994 497176.519874672290532.38055071498473.500337238
2290891.22671147498630.927581145
#Sta/Elev= 30
       0 2469.67   101.4 2469.89   123.9 2466.51   138.6 2466.52   147.8 2463.98
   183.2 2459.61   205.5 2458.12   302.3 2457.53   332.8 2458.63   375.5 2458.59
   396.3 2461.09   436.2 2456.16   456.2 2455.61   489.4 2454.73   517.8 2456.81
   570.1 2457.15   648.1 2458.17   688.6 2455.19   720.7 2457.38   729.4 2456.67
   733.9 2454.73   755.5 2453.41   797.7 2454.92   808.3 2458.04   845.1 2456.89
   878.3 2458.65   946.7 2457.49  1359.1 2457.11    1471 2458.54  1929.9 2459.78
#Mann= 9 ,-1,0
       0     .05       0   101.4     .06       0   205.5     .05       0
   332.8     .07       0   456.2      .1       0   570.1     .08       0
   733.9    .045       0   797.7     .08       0   946.7     .05       0
#XS Ineff= 2 , 0
             353    2460 1551.46         2460.05
Permanent Ineff=
       F       F
Bank Sta=733.9,797.7
XS Rating Curve= 0 ,0
Exp/Cntr=0.3,0.1

Type RM Length L Ch R = 1 ,19368   ,116.3,117.9,117.6
XS GIS Cut Line= 3
2289638.90042063497942.3540023662290282.65411669498549.737433105
2290879.97058049498992.806268444
#Sta/Elev= 30
       0 2465.88    84.2 2465.05    99.1 2457.96   117.2 2453.13   128.2 2451.29
     144 2454.93   161.5 2453.45   177.7 2453.54   188.7 2452.16   216.2 2455.72
   243.1 2452.07   254.7 2453.31   266.1 2456.46   287.7 2455.28   308.5 2455.82
   326.2  2453.9   370.2  2453.2   384.22451.511   413.2 2450.28   418.92451.522
   425.2 2455.09     433 2456.01   612.2 2454.04   786.7 2455.29   834.8 2456.58
   964.7 2455.61  1150.9 2457.41  1355.1 2456.94  1494.6 2458.75  1628.8 2458.41
#Mann= 5 ,-1,0
       0     .06       0     240     .08       0     380     .05       0
   384.2    .045       0   418.9     .05       0
#XS Ineff= 2 , 0
                         1207.77         2458.28
Permanent Ineff=
       F       F
Bank Sta=384.2,418.9
XS Rating Curve= 0 ,0
Exp/Cntr(USF)=0,0
Exp/Cntr=0.3,0.1

Type RM Length L Ch R = 1 ,19250   ,175.5,173,167.6
XS GIS Cut Line= 4
2289596.07397481498038.9876638552289760.00271948498213.074379528
2290159.43653986498597.4369417752290844.09555601499073.026973651
#Sta/Elev= 30
       0 2466.12   112.9  2465.6   117.6 2464.61   128.5 2456.35   137.4 2451.31
   145.9 2450.03   154.4 2450.48   163.5 2453.52   175.2 2454.32   208.2 2454.56
   221.9 2453.52   239.3 2455.07   259.1    2453   273.3 2454.03   285.4 2450.98
   300.4 2452.81     320 2453.45342.91762451.057   350.4 2449.62   372.6 2449.55
382.49672451.091   397.7 2455.27   625.8 2452.99   712.3 2455.59   804.1 2456.24
   916.1  2455.1  1047.6 2456.22  1061.1 2455.13    1072  2456.5  1627.1 2457.75
#Mann= 5 ,-1,0
       0     .06       0     180     .08       0342.9176    .045       0
382.4967     .08       0  589.12     .05       0
#XS Ineff= 2 , 0
                         1201.69         2457.57
Permanent Ineff=
       F       F
Bank Sta=342.9176,382.4967
XS Rating Curve= 0 ,0
Exp/Cntr=0.3,0.1

Type RM Length L Ch R = 1 ,19077   ,610.4,614.7,609.9
XS GIS Cut Line= 4
2289544.33773082498066.0129044332289617.07826145498327.878814691
2290086.25468399 498695.218494362290771.26683385499109.733849862
#Sta/Elev= 30
       0 2466.27    41.4 2466.59   200.2 2464.16   271.8  2461.8   306.3 2460.72
   326.5 2457.65     357 2456.57   367.2 2453.75   375.9 2449.06   411.7 2448.19
   420.2 2449.01   425.9 2450.89   449.1 2453.61   463.7 2453.28   471.5 2450.94
   477.2 2450.71   509.4 2454.98   522.8 2454.99   565.3  2453.7   580.5 2451.42
   595.8 2453.24   624.3 2453.87   782.1 2451.55   829.5 2454.41   854.9 2454.87
  1052.2 2455.22    1113 2453.36  1141.9  2454.7  1394.8  2457.2  1668.3 2457.08
#Mann= 7 ,-1,0
       0     .06       0   200.2     .05       0   271.8     .06       0
   375.9    .045       0   420.2     .06       0   522.8     .08       0
   998.2     .05       0
#XS Ineff= 2 , 0
                          1162.2         2457.44
Permanent Ineff=
       F       F
Bank Sta=375.9,420.2
XS Rating Curve= 0 ,0
Exp/Cntr(USF)=0,0
Exp/Cntr=0.3,0.1

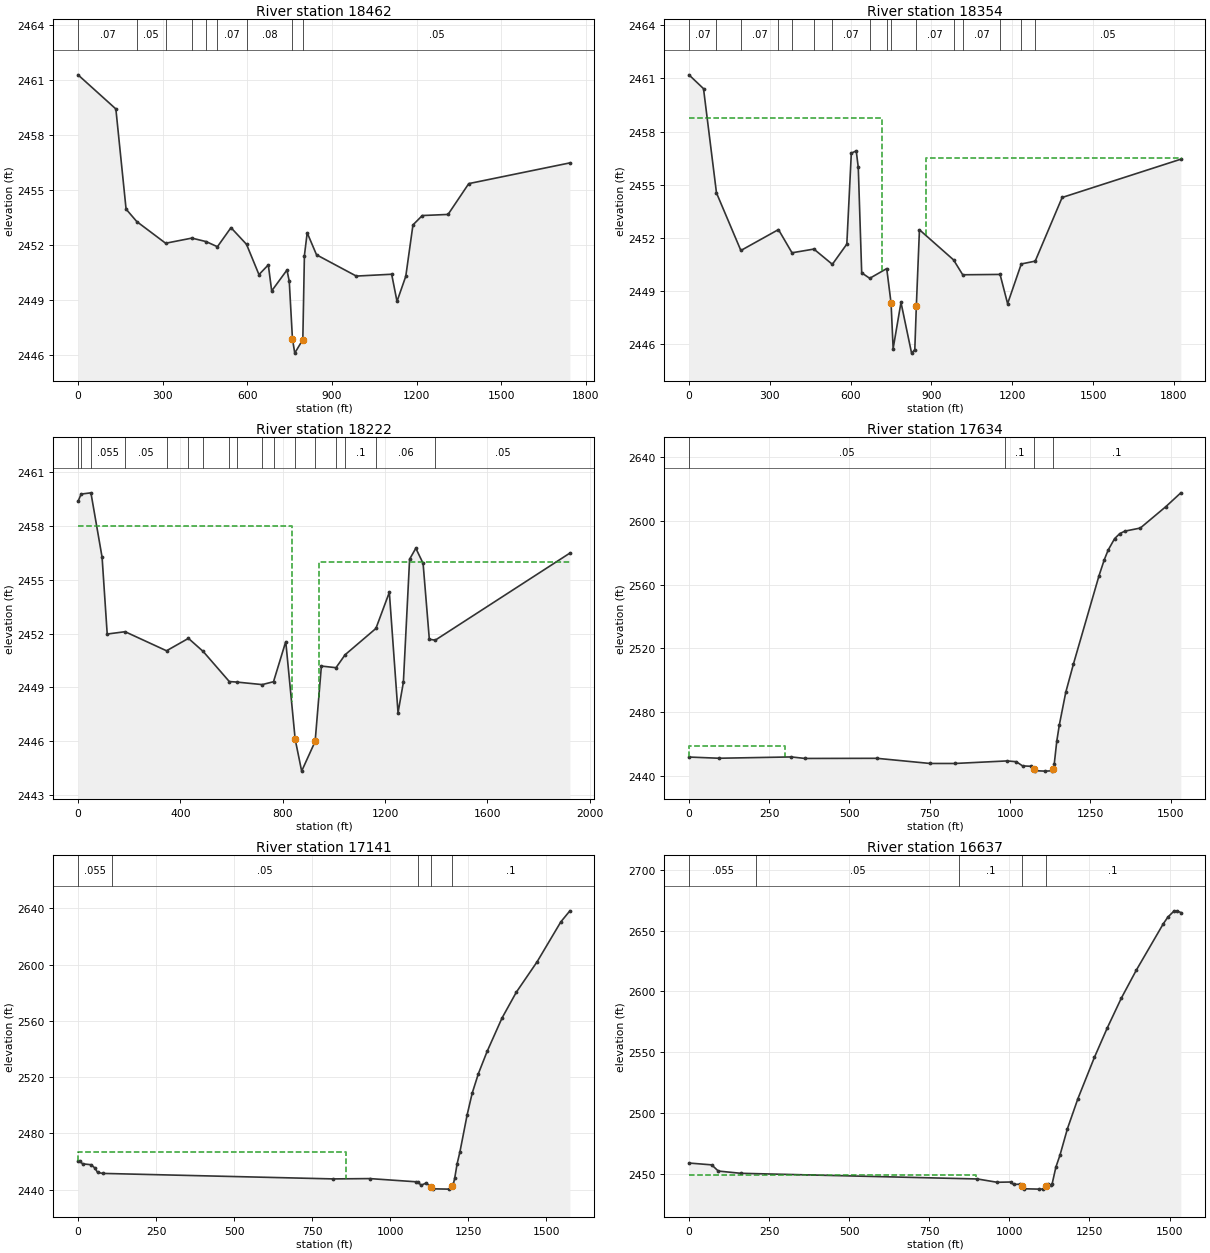
Type RM Length L Ch R = 1 ,18462   ,103.7,108.8,111.3
BEGIN DESCRIPTION:
structure xs 4
END DESCRIPTION:
XS GIS Cut Line= 3
2289358.84937772498407.8933983822290282.65411668499284.416792442
 2290743.8087012499192.914512308
#Sta/Elev= 30
       0 2461.27  134.16 2459.41   170.4 2453.95  208.39 2453.27  310.61 2452.09
  403.62 2452.37  453.97 2452.18  494.16  2451.9  542.26 2452.94  597.34 2452.03
  641.45 2450.38  674.53 2450.91  686.56 2449.49   740.7 2450.63  748.81 2450.02
   760.12446.887  768.27  2446.1   796.92446.836  802.57 2451.42  812.38 2452.66
  845.47 2451.46  986.48  2450.3 1111.85  2450.4 1130.78 2448.92  1161.9 2450.29
 1187.34 2453.09 1220.42  2453.6 1311.72 2453.66 1385.12 2455.34 1743.61 2456.47
#Mann= 9 ,-1,0
       0     .07       0  208.39     .05       0  310.61     .07       0
  403.62     .06       0  453.97     .05       0  494.16     .07       0
  597.34     .08       0   760.1    .045       0   796.9     .05       0
Bank Sta=760.1,796.9
XS Rating Curve= 0 ,0
Exp/Cntr(USF)=0,0
Exp/Cntr=0.5,0.3

Type RM Length L Ch R = 1 ,18354   ,139.6,131.3,131.3
BEGIN DESCRIPTION:
structure xs 3
END DESCRIPTION:
XS GIS Cut Line= 5
2289284.37954297498472.5052030782289582.93088754498758.702698899
2289815.59503881498979.0130014382290163.56177834499337.274614912
2290744.19266914499221.972026668
#Sta/Elev= 30
       0  2461.2    54.1 2460.42   102.2 2454.54   192.7 2451.29   332.2 2452.47
   382.5 2451.16   463.7 2451.37   532.2 2450.51   585.9 2451.65   602.6 2456.78
   620.8 2456.91   628.4 2455.98   641.1 2450.03   670.9 2449.72     734 2450.27
   750.1 2448.32   757.8 2445.76   786.9 2448.36   826.2  2445.5   838.2  2445.7
   843.9 2448.16   855.4 2452.46     982 2450.76    1016 2449.92  1154.6 2449.94
  1182.6 2448.29  1233.3 2450.53    1285 2450.69  1384.9 2454.281825.393 2456.44
#Mann= 16 ,-1,0
       0     .07       0   102.2     .06       0   192.7     .07       0
   332.2     .05       0   382.5     .06       0   463.7     .03       0
   532.2     .07       0   670.9     .06       0     734     .05       0
   750.1    .045       0   843.9     .07       0     982     .06       0
    1016     .07       0  1154.6     .05       0  1233.3     .06       0
    1285     .05       0
#XS Ineff= 2 , 0
           715.4 2458.78   878.6         2456.48
Permanent Ineff=
       F       F
Bank Sta=750.1,843.9
XS Rating Curve= 0 ,0
Exp/Cntr(USF)=0,0
Exp/Cntr=0.5,0.3

Type RM Length L Ch R = 1 ,18222   ,562.6,588.2,625.7
BEGIN DESCRIPTION:
structure xs 2
END DESCRIPTION:
XS GIS Cut Line= 5
  2289216.846042498497.8502352472289442.92060181498799.882194701
2289934.34571429499263.9248235312290087.37971111499401.102833405
2290742.01163029499290.799420172
#Sta/Elev= 30
       0 2459.34    12.2 2459.75    50.5 2459.82    94.1 2456.24   114.1 2451.97
     184  2452.1     346 2451.04   431.6 2451.73   489.4    2451   591.3 2449.33
   621.1  2449.3   720.1 2449.16   764.1 2449.32     812 2451.55   848.8 2446.12
   874.1 2444.35   926.8    2446   951.2 2450.19  1008.4  2450.1    1044 2450.82
  1164.3 2452.28  1216.8 2454.29  1250.8 2447.59  1271.7 2449.29    1296 2456.13
  1320.3 2456.74  1348.7  2455.9  1373.1 2451.68  1396.3 2451.63  1922.5 2456.47
#Mann= 17 ,-1,0
       0    .055       0    12.2     .07       0    50.5    .055       0
     184     .05       0     346     .06       0   431.6     .05       0
   489.4     .06       0   591.3     .05       0   621.1     .06       0
   720.1     .05       0   764.1     .06       0   848.8    .045       0
   926.8     .07       0  1008.4     .05       0    1044      .1       0
  1164.3     .06       0  1396.3     .05       0
#XS Ineff= 2 , 0
           834.8    2458   940.8            2456
Permanent Ineff=
       F       F
Bank Sta=848.8,926.8
XS Rating Curve= 0 ,0
Exp/Cntr=0.5,0.3

Type RM Length L Ch R = 1 ,17634   ,492.1,493.5,492
XS GIS Cut Line= 3
2289289.26363025498659.2674537392289744.27105042499465.210193263
     2289757.149      500071.347
#Sta/Elev= 30
       0 2451.81    94.1 2451.06   319.1 2451.88   361.7 2450.93   585.6 2451.01
   750.9 2447.78   827.7 2447.77     991 2449.38  1019.4 2448.88    1039 2446.25
  1066.4 2446.01  1074.3 2444.45  1077.5 2443.24  1109.3 2442.97  1129.5 2443.16
  1134.1  2444.3  1137.5 2447.15  1145.5 2461.78  1153.5 2472.01  1173.5 2492.46
  1197.5  2510.3  1277.1 2565.69  1293.6 2575.77  1305.7 2581.82  1325.6 2588.92
  1341.6 2592.07  1357.6 2593.63  1405.6 2595.57  1485.6 2609.09  1531.8 2617.68
#Mann= 4 ,-1,0
       0     .05       0  985.51      .1       0  1074.3    .045       0
  1134.1      .1       0
#XS Ineff= 2 , 0
          298.88 2458.59
Permanent Ineff=
       F       F
Bank Sta=1074.3,1134.1
XS Rating Curve= 0 ,0
Exp/Cntr=0.3,0.1

Type RM Length L Ch R = 1 ,17141   ,469.5,503.9,527.7
XS GIS Cut Line= 2
2289221.10887395498534.754394903      2289275.37500110.242579828
#Sta/Elev= 30
       0 2460.15     6.4 2460.29    14.4  2458.4    42.4 2457.73    54.5 2455.31
    62.5 2452.32    78.5 2451.59   817.8 2447.67     935  2447.9  1083.1 2445.63
  1091.1 2445.33  1099.1  2443.1  1115.1  2444.7    1131 2442.22  1139.1 2440.61
  1189.3 2440.41  1199.1 2442.39  1203.1  2444.3  1207.1 2447.98  1215.1 2458.51
  1224.1 2467.02    1247 2493.08  1263.2 2508.55  1283.2 2522.51  1311.2 2538.32
  1358.9 2562.02  1404.5 2580.28  1471.3 2601.96  1547.3 2630.32  1576.4 2638.18
#Mann= 5 ,-1,0
       0    .055       0     110     .05       0    1090      .1       0
    1131    .045       0  1199.1      .1       0
#XS Ineff= 2 , 0
          860.22 2466.64
Permanent Ineff=
       F       F
Bank Sta=1131,1199.1
XS Rating Curve= 0 ,0
Exp/Cntr=0.3,0.1

Type RM Length L Ch R = 1 ,16637   ,503.8,494.6,482.5
XS GIS Cut Line= 3
2289157.59656303498532.378613396 2288967.2974253499271.387421629
     2288567.526      499931.907
#Sta/Elev= 30
       0 2458.89      71 2457.38    91.7 2452.29   161.9 2450.45   900.5 2445.79
   961.6 2443.08  1003.7 2443.28    1013 2441.26  1031.8  2441.5  1039.5 2440.23
  1047.3 2437.72  1093.6 2437.44  1106.5 2437.53  1113.3 2440.09  1120.6 2441.26
  1129.9 2440.81  1133.7 2441.93  1145.3 2455.56    1158 2465.34  1181.3 2487.11
  1214.1 2511.87  1265.5 2545.74  1305.5 2569.85  1349.2 2594.25  1395.8 2617.18
  1480.3 2655.45  1494.6 2660.96  1513.3 2665.85  1522.7 2666.17  1535.2 2664.78
#Mann= 5 ,-1,0
       0    .055       0     210     .05       0  843.12      .1       0
  1039.5    .045       0  1113.3      .1       0
#XS Ineff= 2 , 0
          896.15 2448.77
Permanent Ineff=
       T       F
Bank Sta=1039.5,1113.3
XS Rating Curve= 0 ,0
Exp/Cntr=0.3,0.1

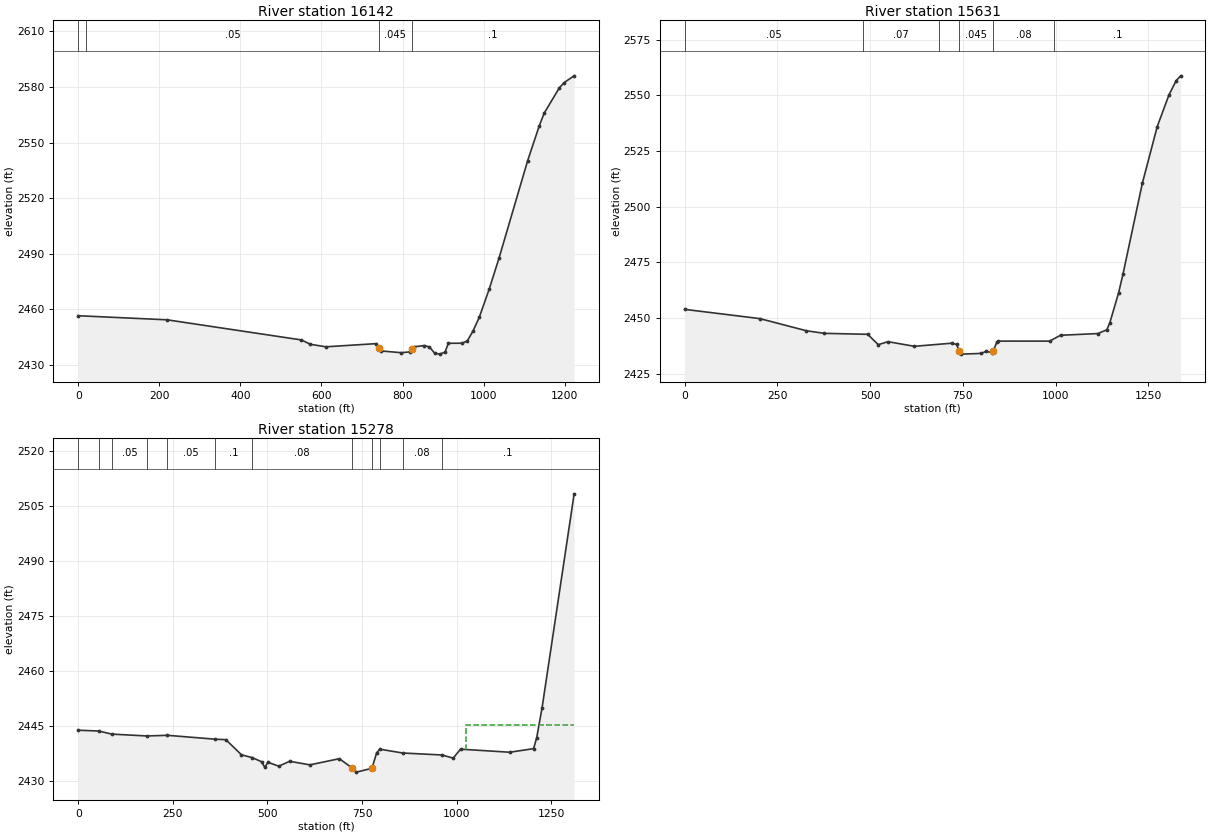
Type RM Length L Ch R = 1 ,16142   ,510.5,511.5,505
XS GIS Cut Line= 3
2288635.71868908498587.0547058582288302.24856811499504.051572909
2288358.93526052      499744.886
#Sta/Elev= 30
       0 2456.63   219.3 2454.42   550.6 2443.56   572.6 2441.21   610.9 2439.86
   734.3 2441.56     741 2438.97   747.1 2437.62   797.2 2436.68   819.1 2437.17
   823.7 2438.81     828 2439.87   853.5 2440.53   866.3 2439.78   879.1 2436.43
   891.8 2435.91   904.6    2437   913.1 2441.76   947.2 2441.81   959.9  2443.1
   974.2 2448.58   989.2 2455.78  1013.9 2471.12  1038.2 2487.94  1108.4  2540.2
  1137.2 2559.11  1149.5    2566  1186.5 2579.51  1198.8 2582.45  1223.2 2586.05
#Mann= 4 ,-1,0
       0    .055       0      20     .05       0     741    .045       0
   823.7      .1       0
Bank Sta=741,823.7
XS Rating Curve= 0 ,0
Exp/Cntr=0.3,0.1

Type RM Length L Ch R = 1 ,15631   ,356.7,352.8,348.1
XS GIS Cut Line= 4
2288287.83574458498567.2180434222287978.98952606498941.951455217
2287818.38949244499454.6361779472287829.56011765499768.158714294
#Sta/Elev= 30
       0 2453.95   202.9 2449.79   327.9 2444.35   376.2 2443.19   493.2 2442.75
   521.8  2438.1   547.9 2439.45   618.9 2437.37   719.5 2438.76     733 2438.19
   739.4 2435.34   744.7 2433.86   799.2 2434.18   812.8 2435.16   828.5  2434.5
   831.9 2435.38   841.1 2439.12   845.3 2439.71   983.6  2439.7  1012.9 2442.32
  1113.5 2443.09  1137.5 2444.75  1145.5 2447.76  1169.5 2461.39  1181.4 2469.85
  1233.5 2510.56  1273.6 2535.97  1305.3 2550.22  1324.6 2556.58  1336.6 2558.74
#Mann= 6 ,-1,0
       0     .05       0     480     .07       0   685.6      .1       0
   739.4    .045       0   831.9     .08       0   995.6      .1       0
Bank Sta=739.4,831.9
XS Rating Curve= 0 ,0
Exp/Cntr=0.3,0.1

Type RM Length L Ch R = 1 ,15278   ,502.5,497.4,467
XS GIS Cut Line= 3
2287874.94255292498487.907982072 2287663.9950141498666.122282109
2287431.22531609499673.578631298
#Sta/Elev= 30
       0 2443.91      54 2443.69    88.7 2442.85   181.4 2442.34   235.6 2442.52
   361.9 2441.46   390.1 2441.33   431.2 2437.21   459.9 2436.44   484.6 2435.31
   492.8 2433.78     501 2435.18   529.7 2434.11   558.5 2435.44     612 2434.47
   689.8 2436.15   722.7 2433.69     735 2432.49     776 2433.54   788.4 2437.76
   796.6 2438.74   857.1  2437.7   960.8 2437.16   990.5 2436.31    1010 2438.74
    1140 2437.91    1203 2438.89  1211.2 2441.88  1225.5 2450.09  1310.1 2508.31
#Mann= 12 ,-1,0
       0      .1       0      54     .08       0    88.7     .05       0
   181.4     .08       0   235.6     .05       0   361.9      .1       0
   459.9     .08       0   722.7    .045       0     776     .08       0
   796.6      .1       0   857.1     .08       0   960.8      .1       0
#XS Ineff= 2 , 0
                         1024.56         2445.25
Permanent Ineff=
       F       F
Bank Sta=722.7,776
XS Rating Curve= 0 ,0
Exp/Cntr(USF)=0,0
Exp/Cntr=0.3,0.1