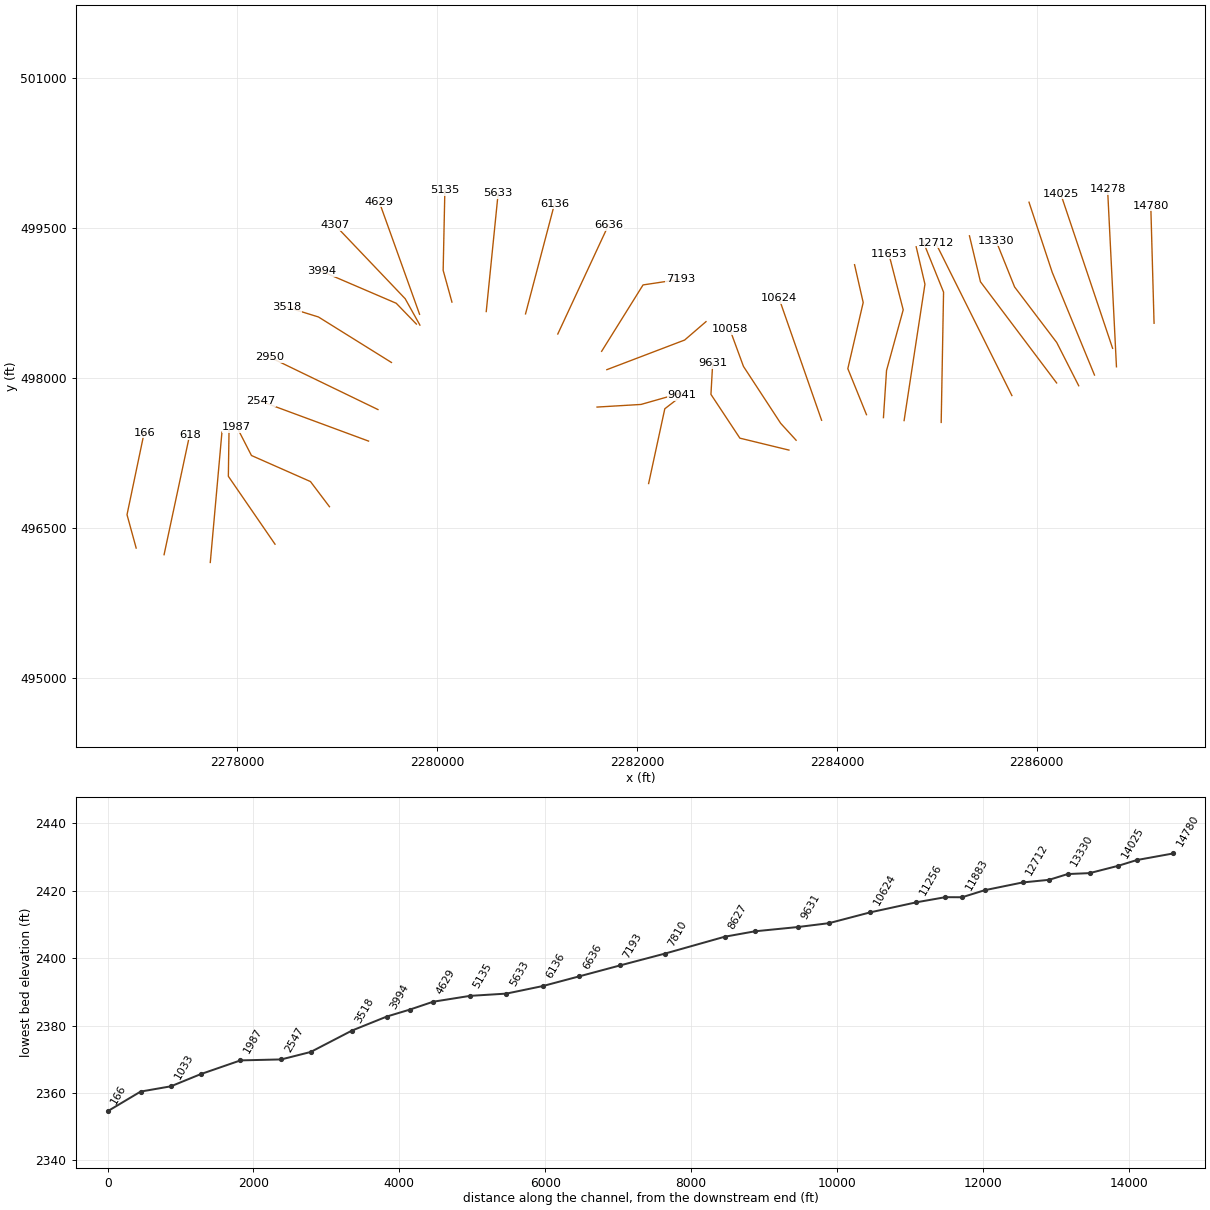
HEC-RAS study SITLNGTNCK.prj: SITLNGTNCK

--- SITLNGTNCK.g01 (geometry) --- (continued)

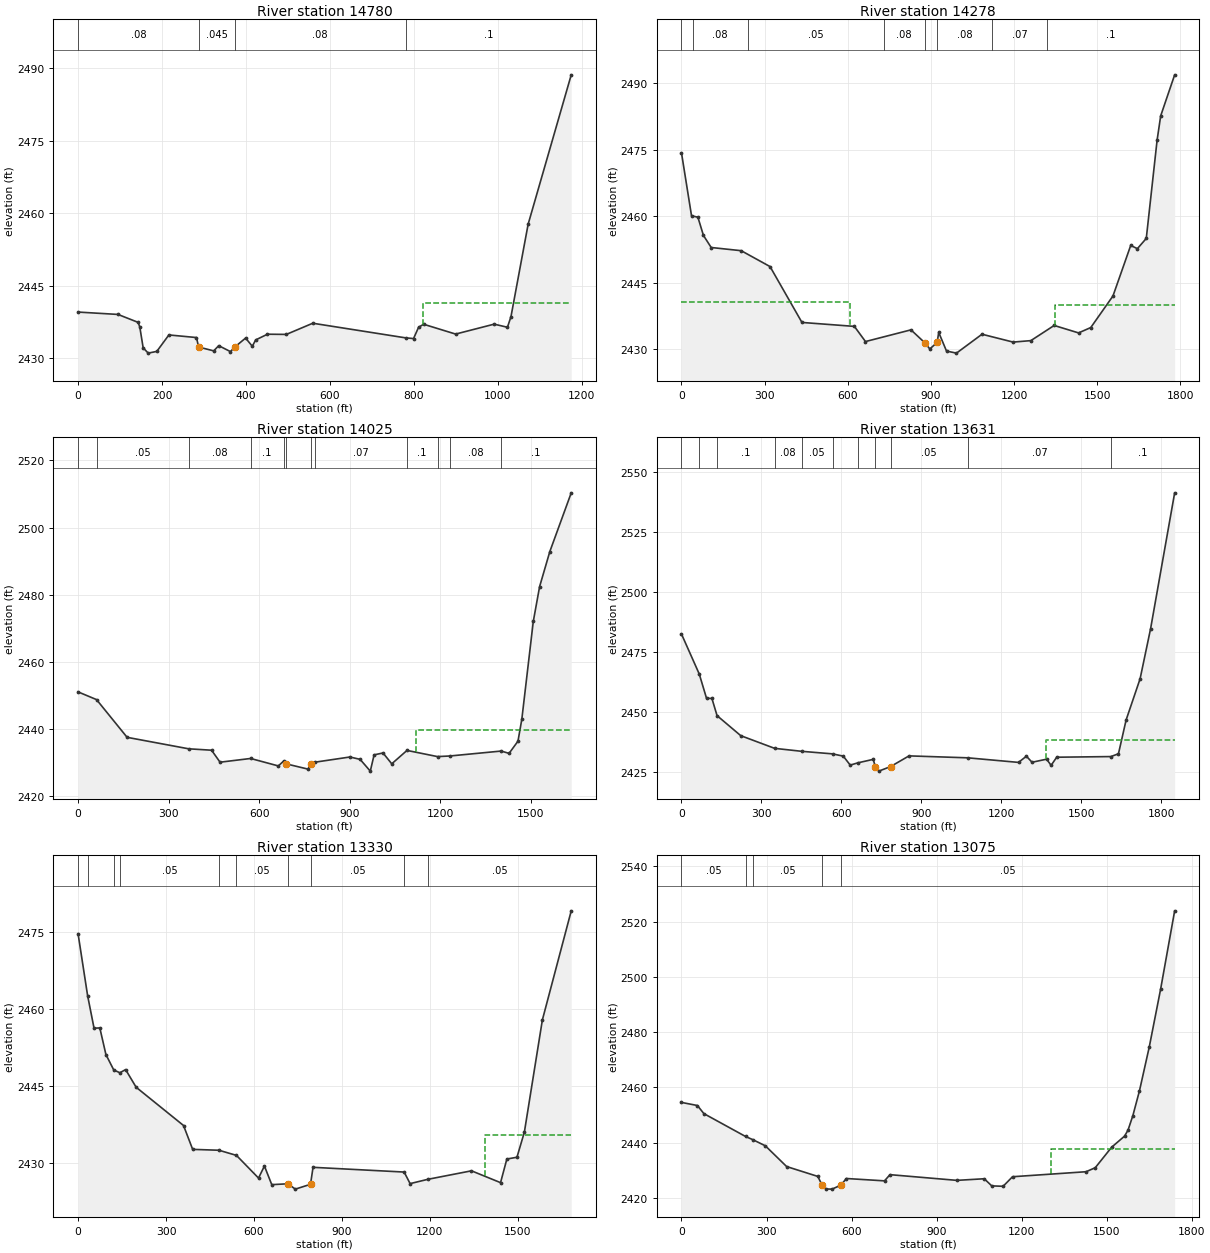
Type RM Length L Ch R = 1 ,14780   ,497,502.3,472.8
XS GIS Cut Line= 2
2287172.99643236498546.1004065742287140.26319358499720.859976206
#Sta/Elev= 30
       0 2439.58    95.1 2439.09   143.1 2437.45   147.1 2436.49   155.1 2432.19
   167.1 2431.09   187.6 2431.45   216.4 2434.85   282.2 2434.31   287.2 2432.35
   323.2 2431.56   335.2 2432.63   363.2  2431.4  373.13 2432.33   399.2  2434.2
   415.2 2432.51   423.2 2433.82   451.3    2435   496.3 2434.96   559.3 2437.27
   780.3 2434.25   799.4  2434.1   811.4 2436.43   823.4 2437.06   899.7 2435.03
   991.5 2437.08  1023.2 2436.44  1031.6 2438.64  1072.5 2457.75  1175.2 2488.63
#Mann= 4 ,-1,0
       0     .08       0   287.2    .045       0  373.13     .08       0
   780.3      .1       0
#XS Ineff= 2 , 0
                          822.08         2441.46
Permanent Ineff=
       F       F
Bank Sta=287.2,373.13
XS Rating Curve= 0 ,0
Exp/Cntr(USF)=0,0
Exp/Cntr=0.3,0.1

Type RM Length L Ch R = 1 ,14278   ,226.7,253.1,255.9
BEGIN DESCRIPTION:
riverline is more dominant in imagery along this path
END DESCRIPTION:
XS GIS Cut Line= 2
2286796.90955672498110.0935905962286708.14360159499887.430101102
#Sta/Elev= 30
       0 2474.28    36.2  2460.1    59.2 2459.77    79.2 2455.66   107.2 2452.94
   215.4 2452.22   319.5 2448.64   434.7 2436.04   623.9 2435.15   663.9 2431.73
   828.1 2434.37   877.2  2431.5   896.2 2430.06  922.58 2431.55   928.2 2433.79
   956.3 2429.59   992.3 2429.12  1084.4 2433.38  1196.6 2431.61  1260.7 2431.94
  1344.8 2435.36  1432.9 2433.68  1476.9 2434.89    1557 2442.01    1621  2453.4
  1645.1 2452.68  1677.2 2454.99  1716.3 2477.17  1729.2 2482.63  1779.6 2491.88
#Mann= 8 ,-1,0
       0     .06       0      40     .08       0     240     .05       0
     730     .08       0   877.2    .045       0  922.58     .08       0
    1120     .07       0    1320      .1       0
#XS Ineff= 2 , 0
          608.45  2440.6 1347.61            2440
Permanent Ineff=
       F       F
Bank Sta=877.2,922.58
XS Rating Curve= 0 ,0
Exp/Cntr(USF)=0,0
Exp/Cntr=0.3,0.1

Type RM Length L Ch R = 1 ,14025   ,354.6,393.8,380.5
XS GIS Cut Line= 2
2286758.37540779498295.145575909 2286238.2806138499844.518878272
#Sta/Elev= 30
       0 2451.03    61.2 2448.73   162.5 2437.49   366.6 2434.07   442.4 2433.65
   470.5 2430.08   571.8 2431.19   663.6 2428.97   681.5 2430.44   688.8  2429.6
   761.6 2428.03   773.32429.601   786.2  2430.1   900.9 2431.63   934.6 2430.93
   968.4 2427.42     981 2432.27  1010.6 2432.83  1039.5  2429.6    1090 2433.59
  1191.1 2431.75  1231.9 2431.93  1402.1  2433.4  1428.3 2432.71  1457.8 2436.35
  1470.5 2442.86  1508.5 2472.01  1529.5 2482.41  1563.3 2492.83  1634.3 2510.34
#Mann= 12 ,-1,0
       0     .08       0    61.2     .05       0   366.6     .08       0
   571.8      .1       0   681.5     .08       0   688.8    .045       0
   773.3     .08       0   786.2     .07       0    1090      .1       0
  1191.1     .07       0  1231.9     .08       0  1402.1      .1       0
#XS Ineff= 2 , 0
                         1118.54         2439.72
Permanent Ineff=
       F       F
Bank Sta=688.8,773.3
XS Rating Curve= 0 ,0
Exp/Cntr(USF)=0,0
Exp/Cntr=0.3,0.1

Type RM Length L Ch R = 1 ,13631   ,290.4,301.6,314.1
XS GIS Cut Line= 3
2286577.11281513498027.5255545992286154.52268906499055.418991623
2285922.34165546499757.424756356
#Sta/Elev= 30
       0 2482.41    66.7 2465.73    93.9 2455.64   114.2 2455.54   133.5 2448.38
   222.4 2440.03   349.6 2434.74   451.6  2433.5   566.8 2432.44   607.3 2431.48
   633.2 2427.75   662.3 2428.71   719.7 2430.15  727.17 2427.14   740.6 2425.24
   784.6 2427.14     854  2431.6  1074.4 2430.79  1264.9 2428.88  1294.4 2431.47
  1315.5 2428.94  1370.2 2430.22  1387.1 2427.65  1408.1 2431.04  1611.7 2431.31
  1639.9 2432.49  1668.7 2446.61  1721.1 2463.76  1760.5 2484.65  1850.8 2541.31
#Mann= 11 ,-1,0
       0      .1       0    66.7     .06       0   133.5      .1       0
   349.6     .08       0   451.6     .05       0   566.8     .08       0
   662.3     .05       0  727.17    .045       0   784.6     .05       0
  1074.4     .07       0  1611.7      .1       0
#XS Ineff= 2 , 0
                         1366.76         2438.12
Permanent Ineff=
       F       F
Bank Sta=727.17,784.6
XS Rating Curve= 0 ,0
Exp/Cntr=0.3,0.1

Type RM Length L Ch R = 1 ,13330   ,255.5,254.5,257
XS GIS Cut Line= 4
2286419.28607661497920.5628620982286199.61275332 498353.18481509
2285778.19862295498909.0928168632285592.14876752499373.096673181
#Sta/Elev= 30
       0 2474.61    32.5 2462.59    54.5 2456.25    74.2  2456.3      95 2451.13
   121.8 2448.12   142.6 2447.59   162.2  2448.2   198.1 2444.77   359.8 2437.33
     391 2432.69   480.7 2432.52   540.4 2431.52   615.7 2427.11   635.8 2429.45
   660.9 2425.83   716.1    2426   741.2 2424.96   793.1  2425.9   801.7  2429.2
  1112.6 2428.28  1132.9 2426.03  1193.6 2426.87  1342.3 2428.52  1441.5 2426.22
    1463 2430.81  1497.5 2431.16  1522.8 2436.05  1584.3 2457.88  1682.7 2479.07
#Mann= 10 ,-1,0
       0      .1       0    32.5     .08       0   121.8     .06       0
   142.6     .05       0   480.7     .08       0   540.4     .05       0
   716.1    .045       0   793.1     .05       0  1112.6     .07       0
  1193.6     .05       0
#XS Ineff= 2 , 0
                         1388.02         2435.44
Permanent Ineff=
       F       F
Bank Sta=716.1,793.1
XS Rating Curve= 0 ,0
Exp/Cntr(USF)=0,0
Exp/Cntr=0.3,0.1

Type RM Length L Ch R = 1 ,13075   ,370.5,362.8,352.9
XS GIS Cut Line= 3
2286198.38169748497948.6997815072285436.57442022498961.297071564
2285326.62986372499421.278680666
#Sta/Elev= 30
       0  2454.6    56.2 2453.48      79 2450.55   225.9 2442.29   250.9 2441.17
   295.9 2438.91     371 2431.41   481.1 2427.84 496.4912424.592   510.4  2423.3
   531.2 2423.25562.28992424.691   581.8 2427.09   716.4 2426.24   735.6 2428.48
   971.7 2426.42  1068.2    2427  1094.8 2424.42  1134.8 2424.28    1168 2427.73
  1427.4 2429.54  1459.9 2430.99  1517.9 2438.42  1563.2  2442.4  1575.5 2444.57
  1592.7 2449.85  1615.9 2458.79  1650.2  2474.5  1690.6 2495.57  1740.1 2523.87
#Mann= 5 ,-1,0
       0     .05       0   225.9     .06       0   250.9     .05       0
 496.491    .045       0562.2899     .05       0
#XS Ineff= 2 , 0
                          1302.3         2437.65
Permanent Ineff=
       F       F
Bank Sta=496.491,562.2899
XS Rating Curve= 0 ,0
Exp/Cntr=0.3,0.1

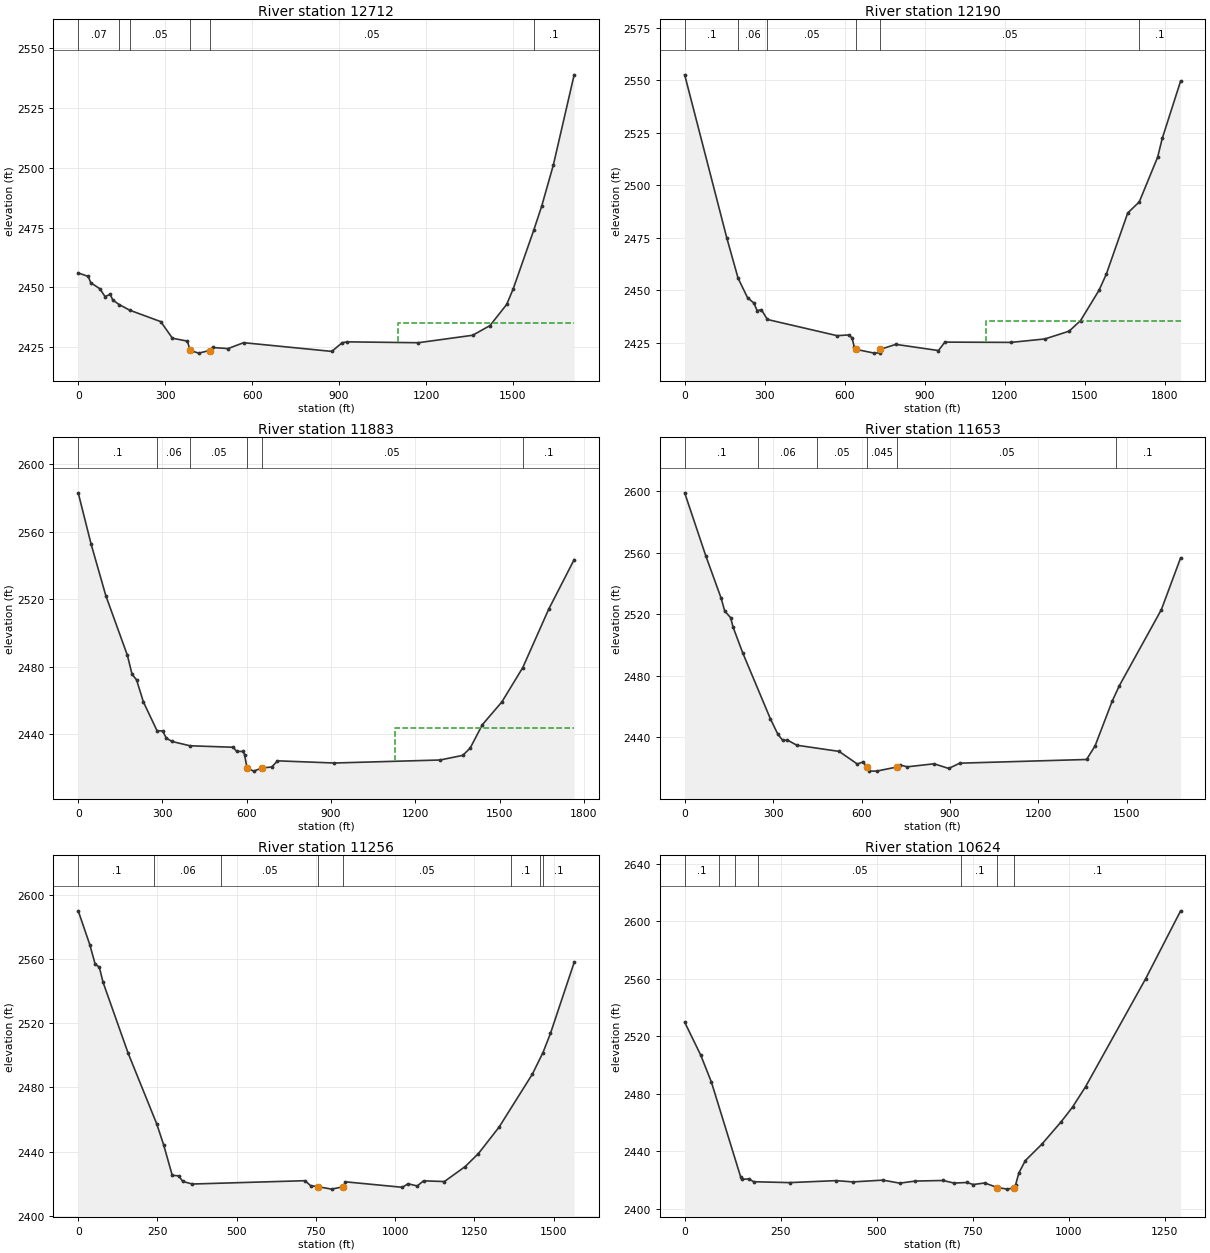
Type RM Length L Ch R = 1 ,12712   ,537.2,522.1,493.8
XS GIS Cut Line= 2
 2285750.9190586497822.3321268312284987.14348701499353.520296538
#Sta/Elev= 30
       0 2456.02    34.5 2454.57    43.4 2451.92    74.7  2449.4    92.6 2446.13
   110.5 2447.07   119.4 2444.65   141.4  2442.8   177.5 2440.44   284.8 2435.65
     325 2428.72     377 2427.48  385.79 2423.61   415.7 2422.47  453.26 2423.56
   463.5 2424.83   516.9 2424.37   570.8 2426.84     875 2423.19   910.6 2426.82
   928.5 2427.19  1173.3 2426.82  1361.1 2429.95  1420.8 2434.01  1478.3 2442.85
  1500.6 2449.28  1572.2 2474.08    1599 2483.93  1639.2 2501.13  1711.1 2538.91
#Mann= 6 ,-1,0
       0     .07       0   141.4     .06       0   177.5     .05       0
  385.79    .045       0  453.26     .05       0  1572.2      .1       0
#XS Ineff= 2 , 0
                         1103.23            2435
Permanent Ineff=
       F       F
Bank Sta=385.79,453.26
XS Rating Curve= 0 ,0
Exp/Cntr(USF)=0,0
Exp/Cntr=0.3,0.1

Type RM Length L Ch R = 1 ,12190   ,301.9,307.5,301.7
XS GIS Cut Line= 3
2285043.88217647  497553.55305042285067.59917289498857.533488823
2284859.90386553499373.105958036
#Sta/Elev= 30
       0 2552.69   158.2 2474.91   200.3 2455.85   235.7 2446.59   259.7 2443.98
   271.7  2440.4   287.7 2440.85   310.3 2436.18   571.7 2428.47   615.7 2428.83
   627.7 2427.42   635.7 2423.25   644.3 2421.91   711.1 2420.16   731.7 2420.31
  734.33 2421.98   791.8 2424.33   951.8 2421.39   975.8 2425.41  1223.8 2425.27
  1351.2 2426.92  1441.8 2430.62  1484.9 2435.69  1553.9 2450.07    1581 2457.67
  1661.7 2486.92  1704.9 2492.17  1773.9 2513.52  1791.1 2522.42    1860 2549.73
#Mann= 6 ,-1,0
       0      .1       0   200.3     .06       0   310.3     .05       0
   644.3    .045       0  734.33     .05       0  1704.9      .1       0
#XS Ineff= 2 , 0
                         1131.27         2435.48
Permanent Ineff=
       F       F
Bank Sta=644.3,734.33
XS Rating Curve= 0 ,0
Exp/Cntr=0.3,0.1

Type RM Length L Ch R = 1 ,11883   ,234.9,229.5,228.3
XS GIS Cut Line= 3
2284672.91942244 497571.89980784 2284881.3849231498937.012602515
 2284793.9639067499311.353877902
#Sta/Elev= 30
       0 2583.19    45.8 2552.83    98.4 2522.12   175.3 2486.68   191.5 2475.62
   207.7 2472.21   232.1 2459.12   280.5 2442.08   300.7  2441.9     313 2437.79
   333.1  2435.7   397.8 2433.12   551.6 2432.25   563.7 2429.84   586.7 2429.74
   592.1 2427.91   600.7    2420   624.4 2418.08   652.8 2419.87   689.2 2420.57
   709.4 2424.19   911.7  2422.9    1288 2424.68    1369 2427.43  1395.4  2431.8
  1438.6 2445.63  1508.2 2459.17  1582.4 2479.48  1674.3 2513.98  1765.4 2543.57
#Mann= 6 ,-1,0
       0      .1       0   280.5     .06       0   397.8     .05       0
   600.7    .045       0   652.8     .05       0  1582.4      .1       0
#XS Ineff= 2 , 0
                          1127.5         2443.75
Permanent Ineff=
       F       F
Bank Sta=600.7,652.8
XS Rating Curve= 0 ,0
Exp/Cntr(USF)=0,0
Exp/Cntr=0.3,0.1

Type RM Length L Ch R = 1 ,11653   ,390.7,397.5,393.5
XS GIS Cut Line= 4
 2284466.3784874497601.5839495612284497.26315604498073.064093803
2284664.04011403498680.461656876 2284519.9347899499242.225294161
#Sta/Elev= 30
       0 2598.96    71.7 2557.98   123.9 2530.38   135.9 2522.07   155.9 2517.84
   163.9 2511.83   196.9 2494.96     291 2451.99   316.3    2442   332.3 2438.15
   348.3 2438.29   380.4 2434.94   523.8 2430.92   585.6 2422.73   605.3 2424.09
   617.8 2420.72   626.1 2418.17   650.7  2418.1   721.5 2420.84   729.8 2422.16
   754.8  2420.9     846 2422.87   895.7 2419.83     933 2423.27  1363.3 2425.67
  1392.1 2434.48    1450 2463.49  1474.2 2473.54    1617 2523.06  1682.3  2556.7
#Mann= 6 ,-1,0
       0      .1       0     250     .06       0     450     .05       0
   617.8    .045       0   721.5     .05       0 1462.37      .1       0
Bank Sta=617.8,721.5
XS Rating Curve= 0 ,0
Exp/Cntr=0.3,0.1

Type RM Length L Ch R = 1 ,11256   ,598.4,632.2,650
XS GIS Cut Line= 4
2284296.60330254497631.339831908 2284110.1758955498091.594866913
2284263.79352943498753.6277899432284177.46800842499132.210672291
#Sta/Elev= 30
       0 2590.01    36.5 2568.94    53.3 2556.94    66.7 2554.81    78.5 2545.41
   157.3  2501.4   247.5 2457.33   269.6 2444.13   296.6  2425.2     317 2424.84
     330 2421.34   360.2 2419.76   715.8 2421.84   732.9 2418.73   756.9 2418.09
   799.5 2416.58   834.9 2418.02   843.1 2421.13  1022.8 2417.72  1040.2 2419.92
  1069.5 2418.57  1089.5 2421.75  1155.2 2421.31  1220.9 2430.68  1262.4 2438.72
  1327.5 2455.18  1432.8 2488.29  1466.2 2501.72  1489.7 2513.58  1564.5 2557.84
#Mann= 8 ,-1,0
       0      .1       0     240     .06       0     450     .05       0
   756.9    .045       0   834.9     .05       0  1366.2      .1       0
  1456.2     .05       0  1466.2      .1       0
Bank Sta=756.9,834.9
XS Rating Curve= 0 ,0
Exp/Cntr=0.3,0.1

Type RM Length L Ch R = 1 ,10624   ,556.3,565.8,573.7
XS GIS Cut Line= 2
 2283847.6634874497575.334336106     2283422.327      498795.007
#Sta/Elev= 30
       0 2529.69    41.9 2506.71    69.7 2487.95   145.5 2422.36   150.2 2420.45
   167.2  2420.7   179.9 2418.75   273.1 2418.13   394.1 2419.51   438.3 2418.62
   516.2 2419.86   560.1 2417.76     601 2419.22   673.2 2419.61   701.5 2417.81
   734.8 2418.21   751.7 2416.81   781.4 2417.87   814.5  2414.7   840.7  2413.6
   858.5 2414.69   861.7 2416.37   870.4 2424.86   887.3 2433.47   929.7 2444.68
   980.5 2460.41  1010.2 2470.65  1044.1 2484.82  1200.7 2559.94  1291.7 2607.11
#Mann= 7 ,-1,0
       0      .1       0      90     .06       0     130     .07       0
     190     .05       0     720      .1       0   814.5    .045       0
   858.5      .1       0
Bank Sta=814.5,858.5
XS Rating Curve= 0 ,0
Exp/Cntr=0.3,0.1

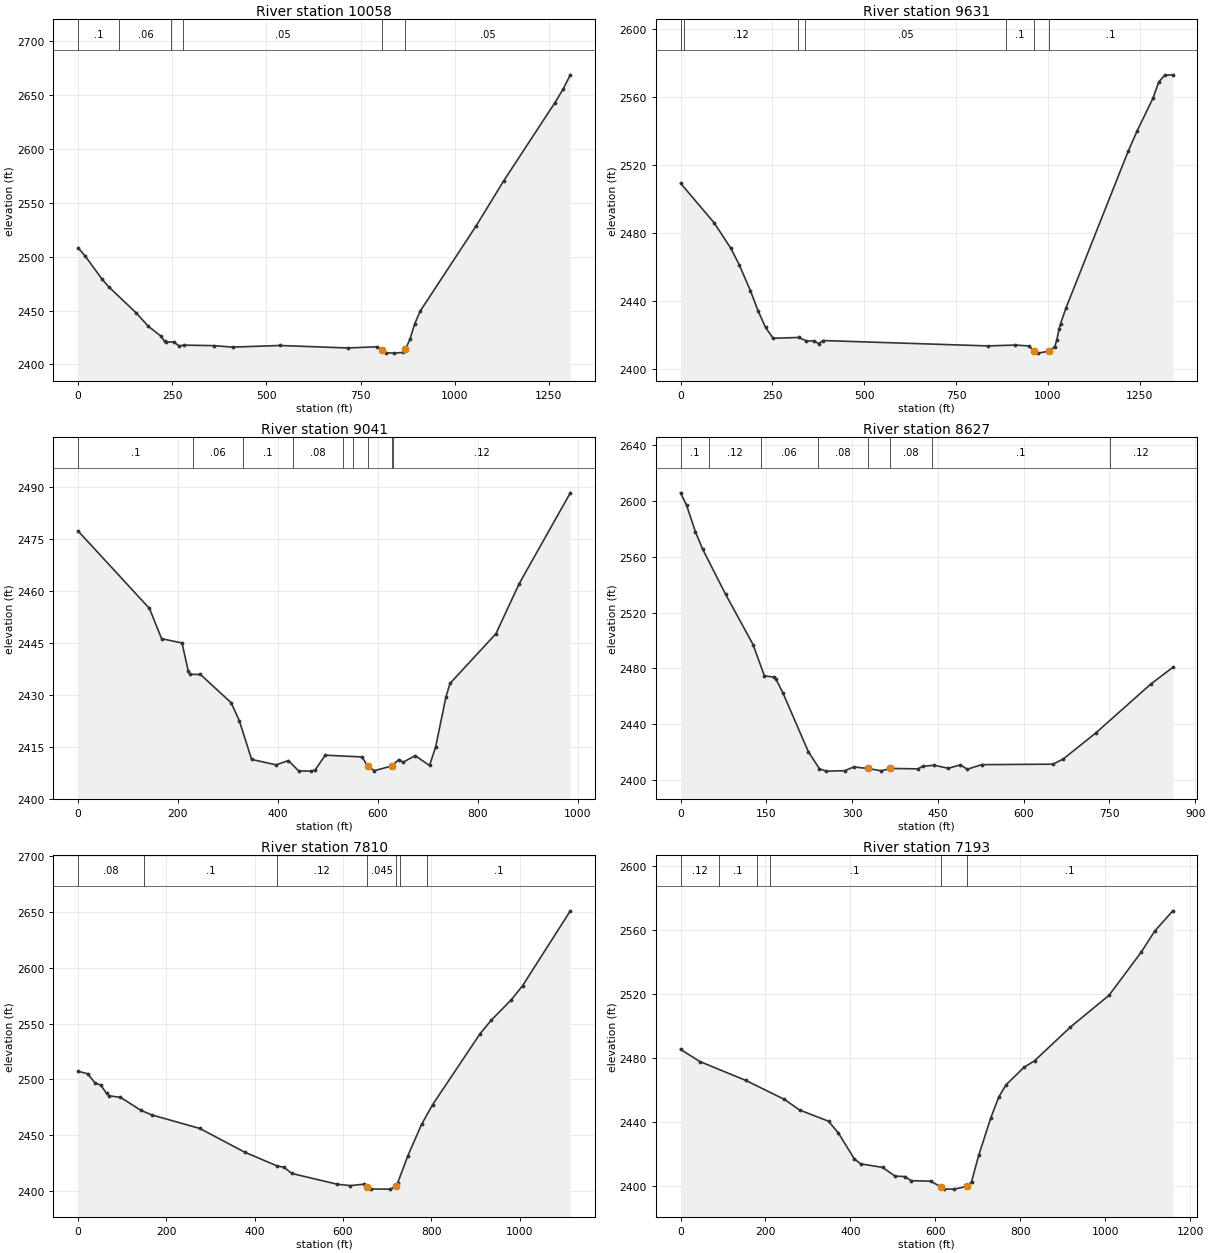
Type RM Length L Ch R = 1 ,10058   ,426,427,428.1
XS GIS Cut Line= 4
2283592.72988237497375.4222856862283438.95011394497543.907572752
2283066.27567693498114.2435896042282929.25652941498487.591378149
#Sta/Elev= 30
       0 2508.35    18.6 2500.81    63.9 2479.09    80.9 2472.23   154.5 2447.74
   186.5 2435.36     219 2426.51   229.6 2421.47   233.9 2420.59   254.2 2420.83
   267.9 2417.14   282.2 2417.84   361.1 2417.33   410.2 2415.99   535.4 2417.48
     717 2415.18   793.5 2416.29   807.8 2413.34   817.4  2410.7   837.9 2410.39
   862.1 2410.98   869.4 2414.21   881.3 2423.24   893.8  2437.5   908.1 2449.23
  1057.4 2528.86  1129.8 2570.27  1266.2 2643.16  1287.4 2655.39  1307.1 2669.01
#Mann= 6 ,-1,0
       0      .1       0     110     .06       0  248.11     .08       0
  278.11     .05       0   807.8    .045       0   869.4     .05       0
Bank Sta=807.8,869.4
XS Rating Curve= 0 ,0
Exp/Cntr=0.3,0.1

Type RM Length L Ch R = 1 ,9631    ,620.2,589.8,559.8
XS GIS Cut Line= 4
2283521.12154626497276.5587647512283030.47070224497396.029438561
2282741.07335294497834.2375462212282758.36523529498143.283932747
#Sta/Elev= 30
       0 2509.34    91.5    2486   136.8 2471.06   160.2 2461.11   190.4 2445.96
   210.9 2434.25   231.5 2424.35   252.1 2417.99   322.1 2418.46   342.7  2416.4
   363.3  2416.4   375.6 2414.87     388 2416.65   836.6 2413.49   911.6    2414
   949.2 2413.43   961.8 2410.25   972.3 2409.24  1002.7 2410.36  1018.5 2413.12
  1024.1 2417.02  1030.1 2423.44  1034.2 2426.56  1049.1 2435.88    1218 2528.01
  1242.1 2539.87  1285.5 2559.25  1301.4  2568.9  1317.5 2572.91  1339.7 2573.13
#Mann= 7 ,-1,0
       0      .1       0      10     .12       0     320     .06       0
     340     .05       0  884.99      .1       0   961.8    .045       0
  1002.7      .1       0
Bank Sta=961.8,1002.7
XS Rating Curve= 0 ,0
Exp/Cntr=0.3,0.1

Type RM Length L Ch R = 1 ,9041    ,461,414,371.4
XS GIS Cut Line= 3
2282117.77510447496941.7518522522282279.58360958497690.258480385
2282453.14141162 497824.17155208
#Sta/Elev= 30
       0 2477.39   142.9 2454.99   167.2 2446.25   208.1 2445.01   220.4 2436.99
   224.5 2435.95     245  2435.9   306.3 2427.75   322.7 2422.56   347.3 2411.35
   396.4 2409.79   420.9 2411.03   441.4 2408.04   465.7 2407.97   474.1 2408.23
   494.6 2412.58   568.3 2412.07   579.3 2409.48   592.8  2408.1   627.4 2409.45
   641.9 2411.32   650.1 2410.53   674.7 2412.44   703.3  2409.6   715.6 2415.03
     736 2429.31   744.2 2433.32   836.1 2447.68   882.7 2462.17     985 2488.41
#Mann= 9 ,-1,0
       0      .1       0     230     .06       0     330      .1       0
     430     .08       0     530      .1       0     550     .08       0
   579.3    .045       0   627.4     .08       0     630     .12       0
Bank Sta=579.3,627.4
XS Rating Curve= 0 ,0
Exp/Cntr=0.3,0.1

Type RM Length L Ch R = 1 ,8627    ,789.2,817,836.6
XS GIS Cut Line= 3
2281601.64242283497707.1680838862282041.52031864  497733.4294508
2282445.66700004497848.663436985
#Sta/Elev= 30
       0    2606    10.6  2597.1    26.1 2578.09    38.6 2565.68    78.7 2533.37
   126.8 2497.18   146.8 2474.67   162.8 2473.86   166.8 2472.44   178.9 2462.67
   223.6 2420.27     243 2408.04     255 2406.36     287 2406.65   303.1 2409.38
   327.1 2408.27   351.2 2406.61     367 2408.28   415.3    2408   423.3 2409.82
   443.4 2410.54   468.4 2408.44   489.2 2410.79   501.7 2407.73   526.6 2411.01
   651.4 2411.34   669.2 2415.03   726.3 2433.77   821.9 2468.62   860.9  2480.8
#Mann= 8 ,-1,0
       0      .1       0      50     .12       0     140     .06       0
     240     .08       0   327.1    .045       0     367     .08       0
     440      .1       0  750.66     .12       0
Bank Sta=327.1,367
XS Rating Curve= 0 ,0
Exp/Cntr=0.3,0.1

Type RM Length L Ch R = 1 ,7810    ,584.8,617,645.1
XS GIS Cut Line= 3
      2281699.94498081.5049075372282478.02347901498378.149336126
2282691.57472269498562.184210076
#Sta/Elev= 30
       0 2507.15    21.6 2504.97    38.8 2496.62    51.6 2494.75    64.5 2487.32
    71.2 2485.08      96  2483.8   142.5 2472.08   167.3 2467.96   275.8 2455.83
     377  2434.6   449.7  2422.4   466.9 2420.83     484 2415.42   586.7 2405.78
   616.7 2404.53   646.7  2405.8   655.2 2403.66   663.8 2401.49   706.6 2401.37
   719.4 2403.78   723.7 2406.99   746.8 2431.37   777.8  2459.5   802.6 2477.07
   910.1 2540.82   935.9 2553.15     981  2571.4  1006.6 2584.07  1114.6 2651.21
#Mann= 7 ,-1,0
       0     .08       0     150      .1       0     450     .12       0
   655.2    .045       0   719.4      .1       0     730     .12       0
     790      .1       0
Bank Sta=655.2,719.4
XS Rating Curve= 0 ,0
Exp/Cntr=0.3,0.1

Type RM Length L Ch R = 1 ,7193    ,551.1,557.2,563.1
XS GIS Cut Line= 3
2281647.89367227 498265.444999982282062.03455982498929.689325567
2282434.02889918 498985.99199998
#Sta/Elev= 30
       0 2485.18    45.9 2477.54   153.9 2465.76   244.8 2453.91   280.3 2447.29
   348.5  2440.3   371.7 2432.91   408.8 2416.92   423.9 2413.65   475.8 2411.42
   505.2 2405.98   528.4  2405.7     543 2403.12   588.9 2402.82   612.5  2399.3
   620.5 2397.94   644.6 2397.85   674.3 2399.59   685.2 2402.51     702  2418.9
   730.3 2442.24   749.4 2455.49   766.5 2463.06   808.8 2474.01   833.5 2478.05
   917.7 2499.06  1009.1 2519.04  1084.3 2545.83  1116.7 2559.21    1159 2571.76
#Mann= 6 ,-1,0
       0     .12       0      90      .1       0     180     .12       0
     210      .1       0   612.5    .045       0   674.3      .1       0
Bank Sta=612.5,674.3
XS Rating Curve= 0 ,0
Exp/Cntr=0.3,0.1

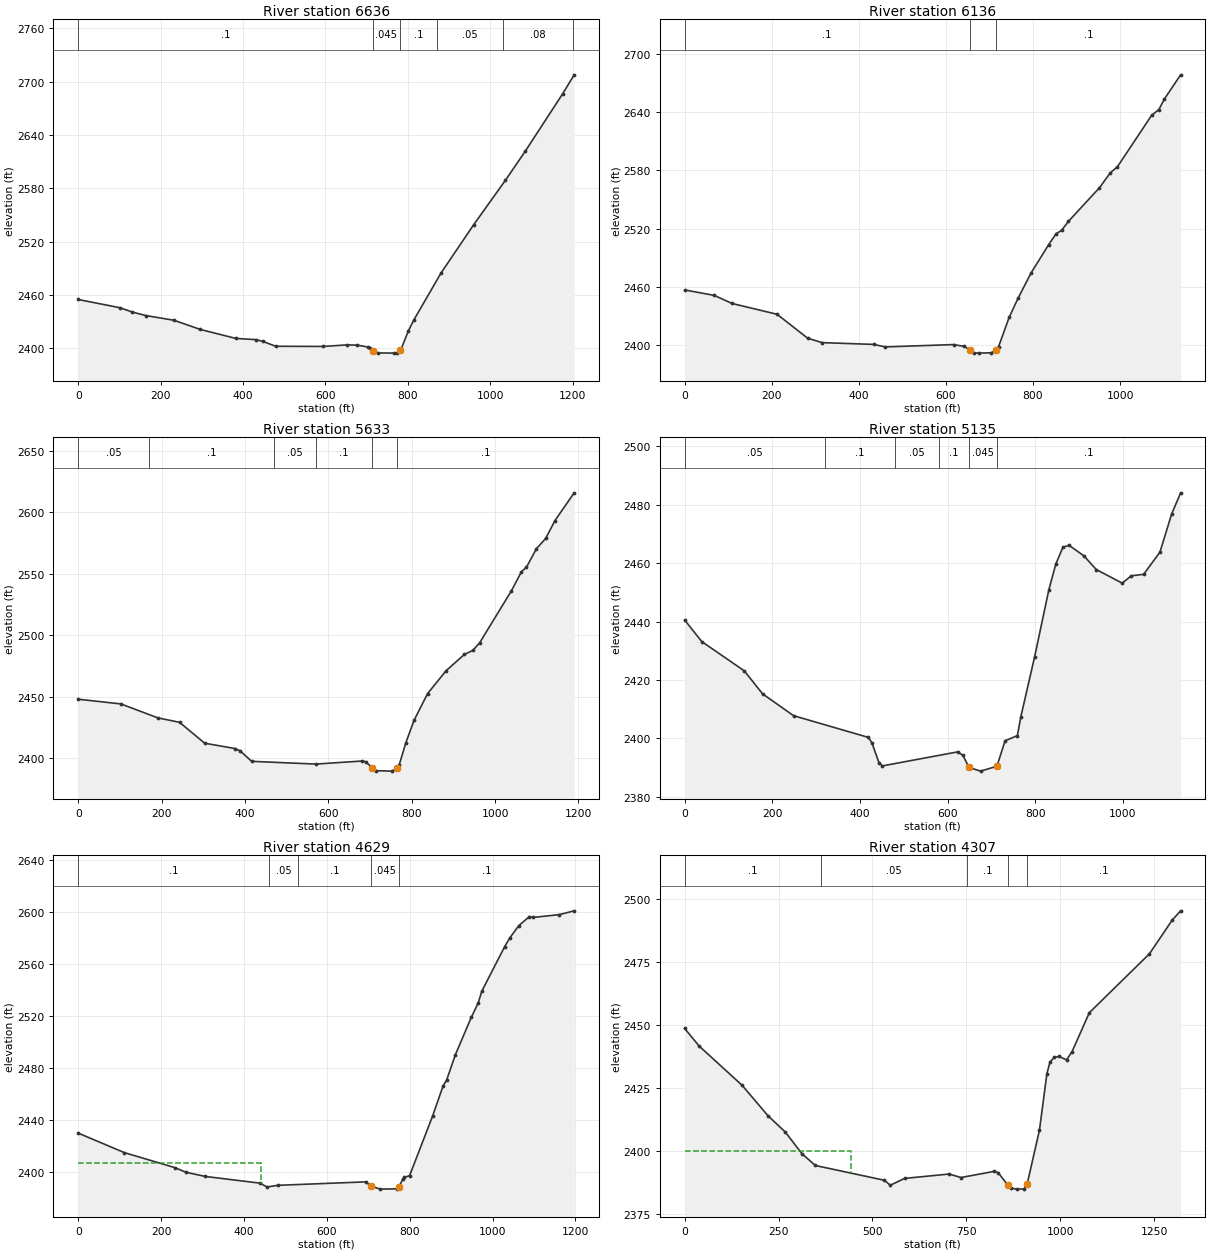
Type RM Length L Ch R = 1 ,6636    ,491.7,499.9,508.2
XS GIS Cut Line= 2
2281209.26448739 498438.39127729     2281716.659      499530.175
#Sta/Elev= 30
       0 2454.97   101.8 2445.66     131 2440.88   163.9 2436.91   232.4 2431.61
   296.4 2421.26   382.4 2411.19   430.9 2409.82   448.6 2407.78   479.4 2402.33
   594.5 2402.15   652.3 2403.87   677.9 2403.58   704.4 2401.42   708.8 2400.38
     715  2397.4   718.7 2395.73     727 2394.86   766.2 2394.62     775 2395.13
  781.27 2397.58   783.8 2399.06   801.4 2419.58   814.3 2431.57   880.8 2484.84
   960.2 2539.24  1037.2 2589.21  1085.4 2621.94  1176.4 2686.76  1203.9  2707.8
#Mann= 6 ,-1,0
       0      .1       0     715    .045       0  781.27      .1       0
     870     .05       0    1030     .08       0    1200      .1       0
Bank Sta=715,781.27
XS Rating Curve= 0 ,0
Exp/Cntr=0.3,0.1

Type RM Length L Ch R = 1 ,6136    ,495.8,502.9,510.1
XS GIS Cut Line= 2
2280886.68268067498639.874722671     2281176.735      499741.521
#Sta/Elev= 30
       0  2456.8    67.8 2451.21   108.9 2442.86   212.3 2431.74   282.6 2407.08
   315.7 2402.55   434.5  2400.7   460.5 2398.14   617.8 2400.55   642.5  2398.6
   654.9 2395.04   663.7 2392.17   675.6 2391.74   704.5 2392.09   716.1 2395.43
   721.1 2398.53   745.5 2428.76   766.6 2448.98   795.5 2474.16   836.3 2503.57
   853.4 2514.75   865.8 2518.11   881.2 2527.29   952.7    2562   977.5 2577.29
   994.1 2583.67  1072.7 2636.68  1089.2 2642.49  1101.6 2653.17  1139.2 2678.31
#Mann= 3 ,-1,0
       0      .1       0   654.9    .045       0   716.1      .1       0
Bank Sta=654.9,716.1
XS Rating Curve= 0 ,0
Exp/Cntr=0.3,0.1

Type RM Length L Ch R = 1 ,5633    ,494.8,498.3,502.1
XS GIS Cut Line= 2
2280493.70437815498663.288403339     2280612.861      499846.959
#Sta/Elev= 30
       0 2447.99   102.4 2444.18   190.9 2432.85   243.1 2429.21   303.4  2412.2
   375.8 2407.89   388.3 2406.02     416 2397.46   570.1 2395.21   681.3 2397.71
   689.4 2397.13   705.3  2392.3   713.5 2389.84   752.8 2389.48   765.7 2391.84
   769.8 2394.27   785.8 2412.48   805.9    2431   838.1  2452.6   882.3  2471.1
   926.5 2484.51   946.7 2487.72   962.7 2493.78  1039.1 2536.17  1063.2 2551.71
  1075.3  2555.4    1099 2570.42  1121.4 2578.82  1143.6 2593.36  1189.7 2615.98
#Mann= 6 ,-1,0
       0     .05       0     170      .1       0     470     .05       0
     570      .1       0   705.3    .045       0   765.7      .1       0
Bank Sta=705.3,765.7
XS Rating Curve= 0 ,0
Exp/Cntr=0.3,0.1

Type RM Length L Ch R = 1 ,5135    ,488.7,505.7,523.6
XS GIS Cut Line= 3
2280150.55489076498757.8435714122280062.77003865499075.876535663
     2280079.839      499877.642
#Sta/Elev= 30
       0 2440.49      39 2433.14   136.2  2423.1   177.7 2415.26   248.5 2407.78
   419.2 2400.35   427.3 2398.51   443.3 2391.75   451.3  2390.6   623.3  2395.4
   635.3 2394.17   648.7 2390.09   675.3 2388.81   712.6 2390.48   731.3  2399.2
   759.3 2400.96   767.3 2407.44   798.8    2428   831.3 2450.95   847.3 2459.77
   863.3  2465.4   877.1  2466.1   911.4 2462.43   939.4 2457.78   998.6 2453.13
  1019.4 2455.65  1047.4 2456.14  1084.7 2463.72  1111.4 2476.79  1131.9 2484.03
#Mann= 6 ,-1,0
       0     .05       0     320      .1       0  479.93     .05       0
  579.93      .1       0   648.7    .045       0   712.6      .1       0
Bank Sta=648.7,712.6
XS Rating Curve= 0 ,0
Exp/Cntr=0.3,0.1

Type RM Length L Ch R = 1 ,4629    ,303.4,321.9,337.9
XS GIS Cut Line= 2
2279826.63694118498636.251352919     2279422.837      499762.976
#Sta/Elev= 30
       0 2430.11   111.5 2415.11   234.7 2403.45   260.2 2400.01   306.9 2396.81
   438.6 2391.67   455.6 2388.73   481.6    2390   693.6 2392.64   706.3 2389.54
   728.4 2387.07   770.1 2387.31   774.3  2388.7   782.8 2394.47   787.1 2396.01
   799.8 2397.51   855.1 2443.05   880.6 2466.39   889.1 2470.84   910.3 2490.38
   948.5 2518.95   965.5  2530.2     974 2539.13  1029.3 2573.47    1042 2580.27
  1063.3 2589.53  1088.8 2596.49  1097.3 2595.81    1161    2598  1196.9 2600.91
#Mann= 5 ,-1,0
       0      .1       0     460     .05       0     530      .1       0
   706.3    .045       0   774.3      .1       0
#XS Ineff= 2 , 0
          440.79 2406.91
Permanent Ineff=
       F       F
Bank Sta=706.3,774.3
XS Rating Curve= 0 ,0
Exp/Cntr=0.3,0.1

Type RM Length L Ch R = 1 ,4307    ,293.6,312.6,327.6
XS GIS Cut Line= 3
2279830.23946701498527.3712785462279682.96867783 498791.65173584
 2278980.7492765 499529.25647474
#Sta/Elev= 30
       0 2448.44    38.7 2441.45   153.2 2425.87   221.9 2413.83   267.7 2407.41
   312.4 2398.77     348  2394.1   531.9 2388.24   547.7 2386.26   585.7 2388.97
   704.5 2390.71   735.9 2389.32   823.4 2391.74   834.7  2391.3   860.1 2386.47
     868 2385.14   884.6 2384.72   904.1  2384.8   912.2 2386.72     945 2408.11
   964.8 2430.51   972.9 2435.08     984 2436.96   996.9 2437.36  1017.1    2436
  1031.7 2439.22  1077.8  2454.7    1238 2478.08  1298.7 2491.46    1321 2495.12
#Mann= 5 ,-1,0
       0      .1       0  362.54     .05       0  752.54      .1       0
   860.1    .045       0   912.2      .1       0
#XS Ineff= 2 , 0
          441.69  2399.9
Permanent Ineff=
       F       F
Bank Sta=860.1,912.2
XS Rating Curve= 0 ,0
Exp/Cntr(USF)=0,0
Exp/Cntr=0.3,0.1

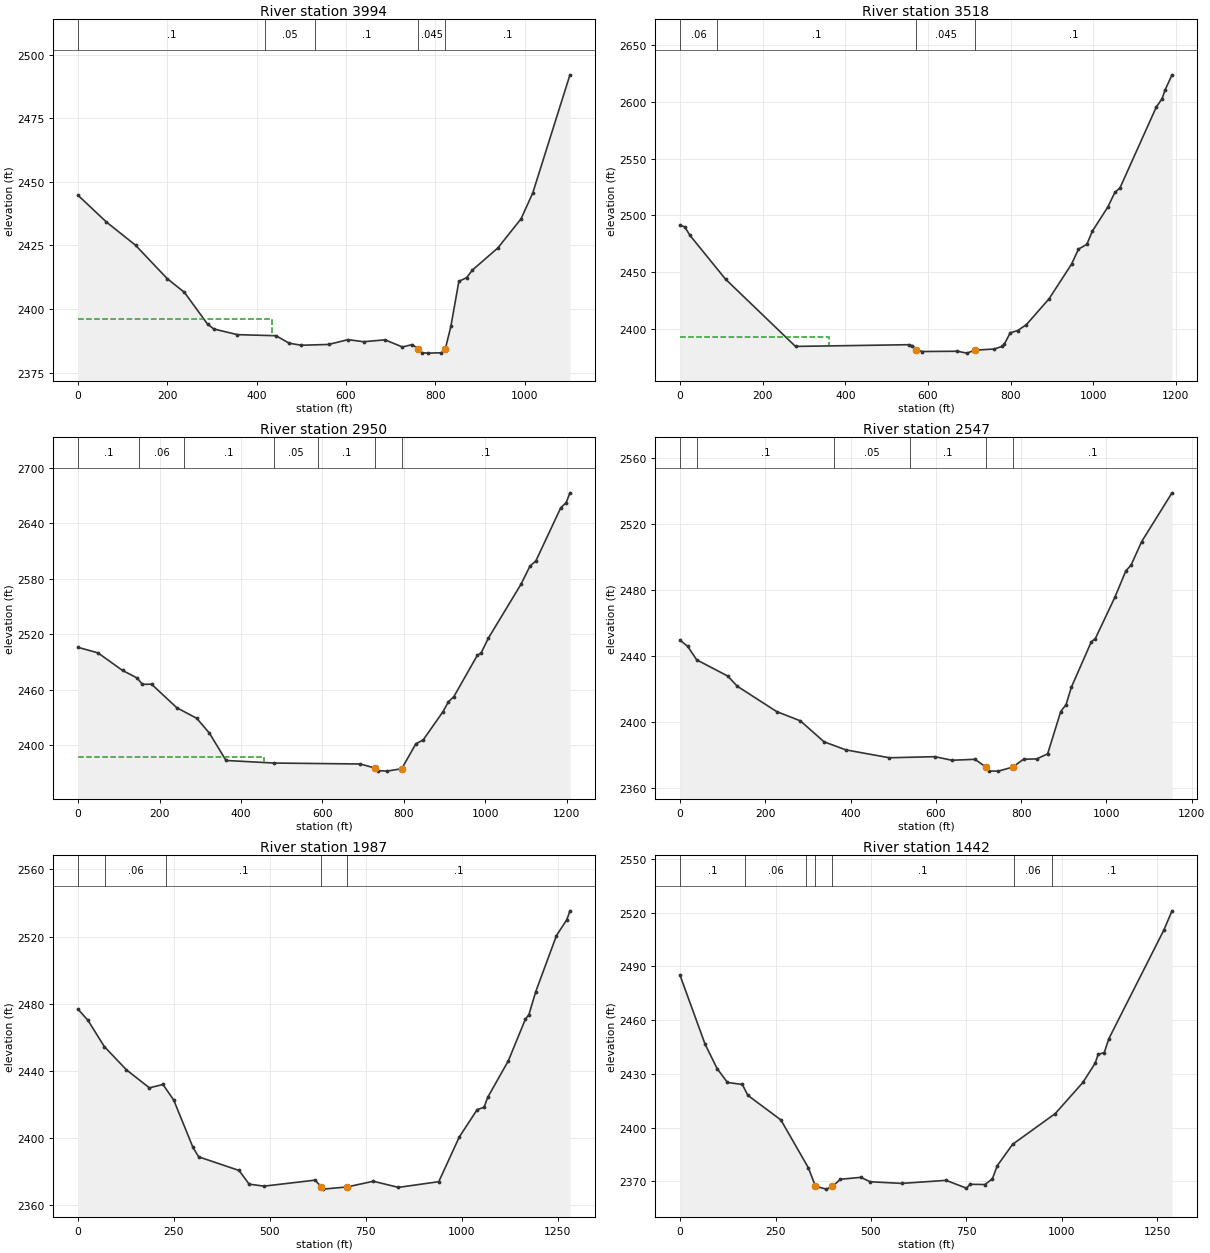
Type RM Length L Ch R = 1 ,3994    ,497.2,476.8,459.4
XS GIS Cut Line= 3
 2279794.8436471498537.9030597882279593.52166763498746.088288563
2278847.71524367499066.373255909
#Sta/Elev= 30
       0  2444.7    63.6 2434.19   128.7 2425.09   199.4    2412   238.3 2406.54
   289.9 2394.11   304.1 2392.16   356.9 2389.94   443.4 2389.52   472.7 2386.57
     500 2385.78     561 2386.09   604.5 2387.98   639.3 2387.16   687.2  2387.9
   726.4 2385.09   748.2 2386.04   761.2 2384.41   769.9 2382.84     783 2382.68
   813.5 2382.82   822.2 2384.28   834.7 2393.19   852.6 2410.86   870.1 2412.37
   883.1 2415.35   939.7 2423.97   991.9 2435.47  1018.1 2445.65  1101.3 2492.03
#Mann= 5 ,-1,0
       0      .1       0  419.61     .05       0  529.61      .1       0
   761.2    .045       0   822.2      .1       0
#XS Ineff= 2 , 0
           434.7 2396.13
Permanent Ineff=
       F       F
Bank Sta=761.2,822.2
XS Rating Curve= 0 ,0
Exp/Cntr(USF)=0,0
Exp/Cntr=0.3,0.1

Type RM Length L Ch R = 1 ,3518    ,555.1,567.6,571.7
XS GIS Cut Line= 3
2279545.47892253498153.5610989732278815.68674693498608.823302557
2278499.97727912498707.196542528
#Sta/Elev= 30
       0 2491.19      11 2490.06    23.9 2482.45     110 2443.81   279.4 2384.45
   553.1 2385.96   562.6 2385.08     572 2381.61   586.1 2379.95     671 2380.18
   694.6 2378.53   713.4 2381.14   760.6 2382.16   779.4 2384.49   784.6 2386.23
   799.1 2396.41   817.1 2398.42   838.2 2403.64   893.2 2426.49   947.6 2457.03
   964.4 2470.35   984.6 2474.48   997.9 2486.09  1035.4 2507.44  1052.4  2520.3
  1064.9 2524.38  1152.9  2595.8  1166.7 2602.95  1173.9 2610.651190.832 2624.11
#Mann= 4 ,-1,0
       0     .06       0      90      .1       0     572    .045       0
   713.4      .1       0
#XS Ineff= 2 , 0
          361.11 2392.99
Permanent Ineff=
       F       F
Bank Sta=572,713.4
XS Rating Curve= 0 ,0
Exp/Cntr(USF)=0,0
Exp/Cntr=0.3,0.1

Type RM Length L Ch R = 1 ,2950    ,400,402.6,409.5
XS GIS Cut Line= 2
2279410.50168629497682.2846470212278323.82054708498208.467093375
#Sta/Elev= 30
       0 2506.02    48.8 2500.09   109.2 2481.07   144.8 2472.96   158.1    2466
   180.4 2466.19   242.6  2440.7   291.5 2429.24   322.6  2413.2   363.2  2383.7
     480 2380.91   692.6 2379.88   728.5 2375.55   735.9 2372.75   758.1 2372.16
   794.4 2374.77   829.2 2401.72     847 2405.82   895.9 2436.56   909.2  2447.2
   922.5 2452.76   980.3 2497.64   989.2 2499.79    1007 2515.85    1087 2574.13
  1109.2 2593.84  1123.8 2599.56  1184.8    2657  1198.1 2662.561207.371 2673.12
#Mann= 7 ,-1,0
       0      .1       0     150     .06       0     260      .1       0
     480     .05       0     590      .1       0   728.5    .045       0
   794.4      .1       0
#XS Ineff= 2 , 0
          455.29 2387.39
Permanent Ineff=
       F       F
Bank Sta=728.5,794.4
XS Rating Curve= 0 ,0
Exp/Cntr(USF)=0,0
Exp/Cntr=0.3,0.1

Type RM Length L Ch R = 1 ,2547    ,563.1,560.3,557.2
XS GIS Cut Line= 2
2279316.70394585497366.5751792082278234.59830617497766.931388391
#Sta/Elev= 30
       0 2449.47      18 2445.67    38.9 2437.55   111.5 2427.74   134.3 2421.49
   226.5 2406.11   282.1 2400.49   337.5 2387.78   388.7 2382.86     491 2378.07
   597.7 2378.73   637.5 2376.55   691.5 2377.14   717.1 2372.49   725.6 2370.02
   746.5 2369.95   779.9 2372.38   805.6 2377.18   836.5 2377.37   862.1 2380.48
   892.8 2406.16   905.3 2410.32   917.5 2420.78   964.4 2448.46   973.8 2450.37
  1019.9 2475.63  1045.5 2491.59  1057.8 2495.11  1082.7  2509.41153.793 2538.96
#Mann= 6 ,-1,0
       0     .06       0      40      .1       0     360     .05       0
     540      .1       0   717.1    .045       0   779.9      .1       0
Bank Sta=717.1,779.9
XS Rating Curve= 0 ,0
Exp/Cntr(USF)=0,0
Exp/Cntr=0.3,0.1

Type RM Length L Ch R = 1 ,1987    ,566,545.4,524.6
XS GIS Cut Line= 4
2278925.49873574496709.9909961492278735.61550509496961.643470492
2278145.37606527497222.446943903 2277998.9600802497508.415664747
#Sta/Elev= 30
       0 2476.76    26.1 2470.06    68.6 2454.49     126  2440.7     186 2429.94
   221.4 2431.96   249.5 2422.62   299.6 2394.44   314.5 2388.87   419.6 2380.77
   445.8 2372.65   484.3 2371.43   617.8 2375.01   633.9 2371.01   638.2 2369.66
  701.84 2370.99   769.4 2374.34     835  2370.7     940  2374.1   993.2 2400.58
    1040 2416.97    1058 2418.35  1067.5 2424.31  1121.2 2446.01  1165.8 2470.88
  1174.8  2473.5  1192.8 2487.27  1246.7 2520.58  1273.7 2530.071281.817  2535.3
#Mann= 5 ,-1,0
       0      .1       0      70     .06       0     230      .1       0
   633.9    .045       0  701.84      .1       0
Bank Sta=633.9,701.84
XS Rating Curve= 0 ,0
Exp/Cntr(USF)=0,0
Exp/Cntr=0.3,0.1

Type RM Length L Ch R = 1 ,1442    ,435.6,408.6,382.3
XS GIS Cut Line= 3
2278381.01429125496334.8000344012277914.31333883497014.261715128
2277921.17658813 497478.67491778
#Sta/Elev= 30
       0 2484.95    65.6 2446.48    97.2 2432.85   124.2 2425.14     163 2424.07
   177.6 2417.96   264.1 2404.23     336 2377.54   354.7 2367.18     383 2365.58
   399.3 2367.12   420.2  2371.1   473.6 2372.16   497.9  2369.7   580.5 2368.78
   696.8 2370.48   750.2 2366.12   759.9  2368.3   798.7 2368.16   818.1 2371.32
   831.2 2378.74   871.2 2390.62   982.8 2407.76  1055.2 2425.15  1087.3 2435.86
  1095.3 2440.82  1111.3 2441.87  1123.3 2449.61  1267.3 2510.25  1288.8 2521.03
#Mann= 7 ,-1,0
       0      .1       0     170     .06       0     330      .1       0
   354.7    .045       0   399.3      .1       0   874.3     .06       0
   974.3      .1       0
Bank Sta=354.7,399.3
XS Rating Curve= 0 ,0
Exp/Cntr(USF)=0,0
Exp/Cntr=0.3,0.1

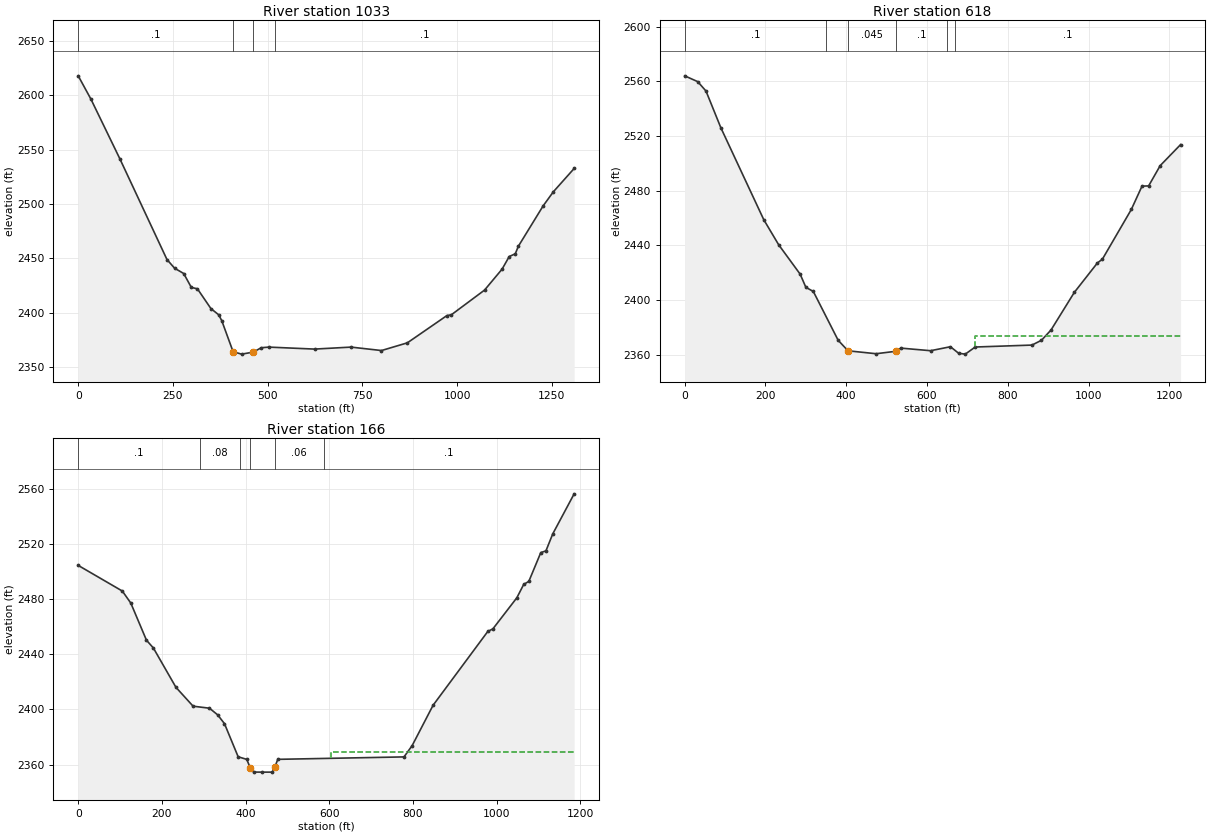
Type RM Length L Ch R = 1 ,1033    ,421.3,415.7,413.4
XS GIS Cut Line= 2
2277733.58110725496151.7800530612277850.25634536497455.797420112
#Sta/Elev= 30
       0 2618.08    33.5 2596.67   109.8 2541.83   234.3 2449.03   254.3 2441.09
   278.5 2436.15   298.6 2423.37   314.7 2422.09   350.2 2403.95   370.9 2398.14
   378.9 2392.81   408.9 2364.16   431.3 2361.97   461.8 2363.78   483.3 2367.86
   503.4 2368.43   623.9 2366.61   720.3 2368.43   800.6 2365.27   868.9 2372.36
   973.1 2397.41   985.3 2398.23  1072.7 2420.91    1119  2440.2  1137.9 2451.81
  1153.8  2454.3    1162 2461.28  1227.5 2498.48  1254.4  2511.41309.227 2532.82
#Mann= 4 ,-1,0
       0      .1       0   408.9    .045       0   461.8     .06       0
     520      .1       0
Bank Sta=408.9,461.8
XS Rating Curve= 0 ,0
Exp/Cntr(USF)=0,0
Exp/Cntr=0.3,0.1

Type RM Length L Ch R = 1 ,618     ,446.8,451.9,462.9
XS GIS Cut Line= 2
2277271.45565437 496229.563545132277527.68362825497430.632172678
#Sta/Elev= 30
       0    2564    32.3 2559.74    52.8 2552.87    89.6 2525.99   195.9 2458.72
   232.7 2440.43   285.9 2418.93   300.1 2409.28   318.6 2406.23     380 2370.57
   404.5 2362.83     474  2360.7   522.8 2362.47   535.4  2364.8     609  2362.9
   658.1 2365.81   678.5 2361.02   694.9  2360.4   719.4  2365.6   859.9 2367.02
   883.5 2370.52   907.1 2378.02   964.8 2405.54  1022.1 2427.12  1034.4 2429.87
    1106 2466.22  1132.5 2483.31  1148.9 2483.47  1177.5  2498.31228.096 2513.71
#Mann= 6 ,-1,0
       0      .1       0     350     .06       0   404.5    .045       0
   522.8      .1       0     650     .05       0     670      .1       0
#XS Ineff= 2 , 0
                          718.91         2374.01
Permanent Ineff=
       F       F
Bank Sta=404.5,522.8
XS Rating Curve= 0 ,0
Exp/Cntr(USF)=0,0
Exp/Cntr=0.3,0.1

Type RM Length L Ch R = 1 ,166     ,,,
XS GIS Cut Line= 3
2276992.35018283496295.9082883662276900.84019216496629.919754313
2277072.42142466497451.221920578
#Sta/Elev= 30
       0 2504.45   105.4 2485.86   125.7 2477.14   163.1 2450.23   179.7 2444.55
   233.6 2416.05   274.6 2402.37   313.7 2400.92   333.1 2396.15   349.6 2389.71
   382.3 2365.69   402.8 2363.82   410.9 2357.92   419.1 2354.61   439.2 2354.57
   464.1 2354.57   470.2 2358.45     477 2363.84   778.7 2365.61   798.1 2373.77
   848.2 2403.06   978.9 2456.54   991.2 2458.46  1048.4 2480.98  1064.8 2490.68
    1077 2492.85  1105.6 2513.72  1117.9 2514.98  1134.2 2527.291185.354 2556.34
#Mann= 6 ,-1,0
       0      .1       0     290     .08       0  386.32      .1       0
   410.9    .045       0   470.2     .06       0  586.32      .1       0
#XS Ineff= 2 , 0
                          603.27         2369.13
Permanent Ineff=
       F       T
Bank Sta=410.9,470.2
XS Rating Curve= 0 ,0
Exp/Cntr(USF)=0,0
Exp/Cntr=0.3,0.1
LCMann Table=0

Chan Stop Cuts=-1
Use User Specified Reach Order=0
Composite Channel Slope=5